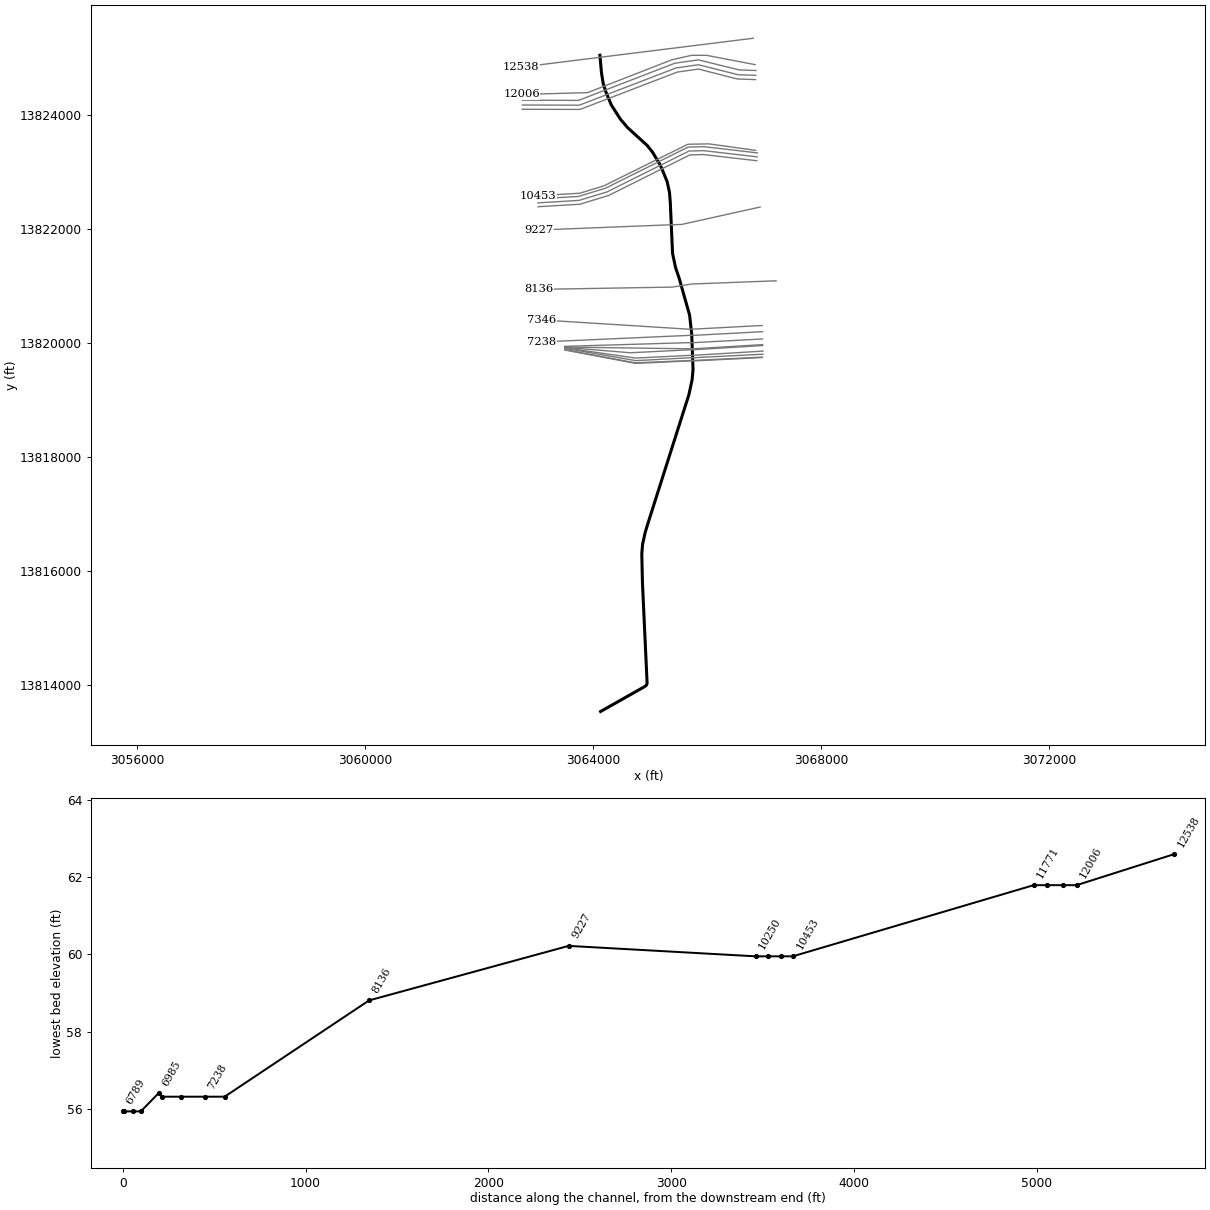
--- D142-00-00.prj (project) ---

Proj Title=D142-00-00
Current Plan=p07
Default Exp/Contr=.3,.1
English Units
Geom File=g03
Flow File=f01
Flow File=f04
Plan File=p06
Plan File=p07
Y Axis Title=Elevation
X Axis Title(PF)=Main Channel Distance
X Axis Title(XS)=Station
BEGIN DESCRIPTION:
Brays Bayou Watershed
Tributary 20.86
HCFCD Unit D142-00-00
Flood Hazard & Floodway Model
10, 2, 1, 0.2% Event
Filename D142.prj
Prepared by: Dodson & Associates, Inc.   Date: December 2003
Reviewed by:____________________	 Date:_________
STATUS (Final RAS)
FOR FLOOD HARZARD RECOVERY DATA ONLY,03/02/2004
Will Be Voided Upon Release of The Preliminary DFIRM
END DESCRIPTION:
DSS Export Rating Curves= 0
DSS Export Rating Curve Sorted= 0
DSS Export Volume Flow Curves= 0
DXF OffsetX= 0
DXF OffsetY= 0
DXF ScaleX= 1
DXF ScaleY= 10

--- D142-00-00.p07 (plan) ---

Plan Title=Floodway
Version=Version 3.0.1  Mar 2001
Short Identifier=Floodway0607
Geom File=g03
Flow File=f04
Subcritical Flow
K Sum by GR= 0
Std Step Tol= 0.01
Critical Tol= 0.01
Num of Std Step Trials= 20
Max Error Tol= 0.3
Flow Tol Ratio= 0.001
Split Flow NTrial= 30
Split Flow Tol= 0.02
Split Flow Ratio= 0.02
Log Output Level= 0
Friction Slope Method= 2
Unsteady Friction Slope Method= 2
Secant Critical Depth
Global Vel Dist= 0 , 0 , 0
Global Log Level= 0
CheckData=True
Encroach Param=-1 ,0,0, 2
Encroach River=D142-00-00
Encroach Reach=Reach 0
Encroach Node=12538
       1 2650.56 2752.26
Encroach Node=12006
       1 2705.37 2816.26
Encroach Node=11931
       1 2693.13 2817.88
Encroach Node=11925.63
       1 2643.13 2817.88
Encroach Node=11846
       1 2680.53 2791.26
Encroach Node=11771
       1 2566.66 2755.25
Encroach Node=10453
       1 1734.55 1869.83
Encroach Node=10388
       1 1738.55 1874.48
Encroach Node=10383.11
       1 1675.55 1874.82
Encroach Node=10318
       1 1675.55 1848.82
Encroach Node=10250
       1 1658.55  1799.2
Encroach Node=9227
       1 1523.31 1643.39
Encroach Node=8136
       1 1606.01 1727.47
Encroach Node=7346
       1 1210.52 1277.23
Encroach Node=7238
       1 1208.45 1270.23
Encroach Node=7120
       1 1150.52 1270.23
Encroach Node=7109
       1 1150.52 1271.01
Encroach Node=7002
       1 1193.52 1264.01
Encroach Node=6985
       1 1202.76 1268.57
Encroach Node=6887
       1 1201.45 1272.79
Encroach Node=6845
       1 1197.45  1261.4
Encroach Node=6804
       1 1183.45  1261.4
Encroach Node=6796
       1 1183.45  1247.4
Encroach Node=6789
       1 1179.45  1243.4
Encroach Node=6366
       1  853.34  928.26
Encroach Node=6134
       1  855.26  946.89
Encroach Node=5890
       1  896.69  969.11
Encroach Node=5850
       1  907.56     972
Encroach Node=5804
       1  907.56     978
Encroach Node=5778
       1  913.56     978
Encroach Node=5582
       1  942.86  1018.9
Encroach Node=4990
       1  639.99  720.22
Encroach Node=4950
       1  648.92   710.1
Encroach Node=4907
       1  648.92   711.1
Encroach Node=4903
       1  649.92   711.1
Encroach Node=4888
       1     648   712.1
Encroach Node=4526
       1  663.06  725.93
Encroach Node=4265
       1   670.2  740.18
Encroach Node=4096
       1  667.44  741.61
Encroach Node=4055
       1  676.89  744.61
Encroach Node=4008
       1  676.89  744.88
Encroach Node=4003
       1  680.89  744.88
Encroach Node=3986
       1  682.89  750.61
Encroach Node=3617
       1  686.61  748.89
Encroach Node=3348
       1 1939.53  2010.9
Encroach Node=2913
       1 1915.04 1992.59
Encroach Node=2445
       1 1883.51 1947.58
Encroach Node=2021
       1 1841.94 1913.66
Encroach Node=1910
       1 1826.06 1916.59
Encroach Node=1829
       1 1822.83 1892.75
Encroach Node=1742
       1 1820.55 1892.75
Encroach Node=1738
       1 1820.55 1889.75
Encroach Node=1659
       1 1818.55  1896.3
Encroach Node=1509
       1 1806.86 1885.08
Encroach Node=1007
       1 1786.47 1851.19
Encroach Node=259
       1 1589.58 1661.98
Encroach Node=203
       1 1589.58 1661.98
Encroach Node=153
       1  1521.4 1608.46
Encroach Node=151
       1  1521.4 1608.46
Encroach Node=150
       1  1521.4 1608.46
Encroach Node=100
       1  1521.4 1608.46
Encroach Reach=D142-00-00_0001
Encroach Node=12538
       1 2650.56 2752.26
Encroach Node=12006
       1 2705.37 2816.26
Encroach Node=11931
       1 2693.13 2817.88
Encroach Node=11925.63
       1 2643.13 2817.88
Encroach Node=11846
       1 2680.53 2791.26
Encroach Node=11771
       1 2566.66 2755.25
Encroach Node=10453
       1 1734.55 1869.83
Encroach Node=10388
       1 1738.55 1874.48
Encroach Node=10383.11
       1 1675.55 1874.82
Encroach Node=10318
       1 1675.55 1848.82
Encroach Node=10250
       1 1658.55  1799.2
Encroach Node=9227
       1 1523.31 1643.39
Encroach Node=8136
       1 1606.01 1727.47
Encroach Node=7346
       1 1210.52 1277.23
Encroach Node=7238
       1 1208.45 1270.23
Encroach Node=7120
       1 1150.52 1270.23
Encroach Node=7109
       1 1150.52 1271.01
Encroach Node=7002
       1 1193.52 1264.01
Encroach Node=6985
       1 1202.76 1268.57
Encroach Node=6887
       1 1201.45 1272.79
Encroach Node=6845
       1 1197.45  1261.4
Encroach Node=6804
       1 1183.45  1261.4
Encroach Node=6796
       1 1183.45  1247.4
Encroach Node=6789
       1 1179.45  1243.4
Encroach Node=6366
       1  853.34  928.26
Encroach Node=6134
       1  855.26  946.89
Encroach Node=5890
       1  896.69  969.11
Encroach Node=5850
       1  907.56     972
Encroach Node=5804
       1  907.56     978
Encroach Node=5778
       1  913.56     978
Encroach Node=5582
       1  942.86  1018.9
Encroach Node=4990
       1  639.99  720.22
Encroach Node=4950
       1  648.92   710.1
Encroach Node=4907
       1  648.92   711.1
Encroach Node=4903
       1  649.92   711.1
Encroach Node=4888
       1     648   712.1
Encroach Node=4526
       1  663.06  725.93
Encroach Node=4265
       1   670.2  740.18
Encroach Node=4096
       1  667.44  741.61
Encroach Node=4055
       1  676.89  744.61
Encroach Node=4008
       1  676.89  744.88
Encroach Node=4003
       1  680.89  744.88
Encroach Node=3986
       1  682.89  750.61
Encroach Node=3617
       1  686.61  748.89
Encroach Node=3348
       1 1939.53  2010.9
Encroach Node=2913
       1 1915.04 1992.59
Encroach Node=2445
       1 1883.51 1947.58
Encroach Node=2021
       1 1841.94 1913.66
Encroach Node=1910
       1 1826.06 1916.59
Encroach Node=1829
       1 1822.83 1892.75
Encroach Node=1742
       1 1820.55 1892.75
Encroach Node=1738
       1 1820.55 1889.75
Encroach Node=1659
       1 1818.55  1896.3
Encroach Node=1509
       1 1806.86 1885.08
Encroach Node=1007
       1 1786.47 1851.19
Encroach Node=259
       1 1589.58 1661.98
Encroach Node=203
       1 1589.58 1661.98
Encroach Node=153
       1  1521.4 1608.46
Encroach Node=151
       1  1521.4 1608.46
Encroach Node=150
       1  1521.4 1608.46
Encroach Node=100
       1  1521.4 1608.46
Computation Interval=1HOUR
Output Interval=1HOUR
Run HTab= 0
Run UNet= 0
Run PostProcess= 0
UNET Theta= 1
UNET ZTol= 0.02
UNET ZSATol= 0.1
UNET MxIter= 20
UNET MaxInSteps= 20
UNET DtIC= 0
UNET DtMin= 0
UNET MaxCRTS= 20
UNET WFStab= 2
UNET SFStab= 1
UNET WFX= 1
UNET SFX= 1
UNET Convert EG Bridges=-1
UNET Use Existing IB Tables=-1
Instantaneous Interval=1HOUR
Write IC File= 0
Write Velocity= 0
Write Detailed= 0

--- D142-00-00.p06 (plan) ---

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Plan Title=FEMA Effective June 2007
Short Identifier=FEMAeff0607
Geom File=g03
Flow File=f01
Encroach Param=-1 ,0,0, 0

--- D142-00-00.f04 (steady flow) ---

Flow Title=Floodway
Version=Version 3.0.1  Mar 2001
Number of Profiles= 2
Profile Names=1PCT_100yr,1PCTFloodway_100yrFW
River Rch & RM=D142-00-00,D142-00-00_0001 ,12538
     802     802
River Rch & RM=D142-00-00,D142-00-00_0001 ,11771
     933     933
River Rch & RM=D142-00-00,D142-00-00_0001 ,10250
    1032    1032
River Rch & RM=D142-00-00,D142-00-00_0001 ,9227
    1149    1149
River Rch & RM=D142-00-00,D142-00-00_0001 ,8136
    1243    1243
River Rch & RM=D142-00-00,D142-00-00_0001 ,7346
    1369    1369
River Rch & RM=D142-00-00,D142-00-00_0001 ,6366
    1479    1479
River Rch & RM=D142-00-00,D142-00-00_0001 ,5582
    1642    1642
River Rch & RM=D142-00-00,D142-00-00_0001 ,4526
    1845    1845
River Rch & RM=D142-00-00,D142-00-00_0001 ,3348
    2104    2104
River Rch & RM=D142-00-00,D142-00-00_0001 ,2021
    2325    2325
River Rch & RM=D142-00-00,D142-00-00_0001 ,1007
    2569    2569
Boundary for River Rch & Prof#=D142-00-00,D142-00-00_0001 , 1
Up Type= 0
Dn Type= 1
Dn Known WS=54.91
Boundary for River Rch & Prof#=D142-00-00,D142-00-00_0001 , 2
Up Type= 0
Dn Type= 1
Dn Known WS=54.91
DSS Import GetInterval= 0
DSS Import GetPeak= 0
DSS Import FillOption= 0

--- D142-00-00.f01 (steady flow) ---

Flow Title=FEMA Effective June 2007
Version=Version 3.0.1  Mar 2001
Number of Profiles= 4
Profile Names=10PCT_10yr,2PCT_50yr,1PCT_100yr,0.2PCT_500yr
River Rch & RM=D142-00-00,D142-00-00_0001 ,12538
     499     699     802    1075
River Rch & RM=D142-00-00,D142-00-00_0001 ,11771
     579     812     933    1252
River Rch & RM=D142-00-00,D142-00-00_0001 ,10250
     639     898    1032    1387
River Rch & RM=D142-00-00,D142-00-00_0001 ,9227
     711    1000    1149    1548
River Rch & RM=D142-00-00,D142-00-00_0001 ,8136
     768    1081    1243    1675
River Rch & RM=D142-00-00,D142-00-00_0001 ,7346
     844    1191    1369    1849
River Rch & RM=D142-00-00,D142-00-00_0001 ,6366
     911    1286    1479    2000
River Rch & RM=D142-00-00,D142-00-00_0001 ,5582
    1010    1428    1642    2223
River Rch & RM=D142-00-00,D142-00-00_0001 ,4526
    1132    1603    1845    2502
River Rch & RM=D142-00-00,D142-00-00_0001 ,3348
    1288    1827    2104    2858
River Rch & RM=D142-00-00,D142-00-00_0001 ,2021
    1422    2019    2325    3164
River Rch & RM=D142-00-00,D142-00-00_0001 ,1007
    1568    2230    2569    3500
Boundary for River Rch & Prof#=D142-00-00,D142-00-00_0001 , 1
Up Type= 0
Dn Type= 3
Dn Slope=.00026
Boundary for River Rch & Prof#=D142-00-00,D142-00-00_0001 , 2
Up Type= 0
Dn Type= 3
Dn Slope=.00026
Boundary for River Rch & Prof#=D142-00-00,D142-00-00_0001 , 3
Up Type= 0
Dn Type= 3
Dn Slope=.00026
Boundary for River Rch & Prof#=D142-00-00,D142-00-00_0001 , 4
Up Type= 0
Dn Type= 3
Dn Slope=.00026
DSS Import GetInterval= 0
DSS Import GetPeak= 0
DSS Import FillOption= 0

--- D142-00-00.g03 (geometry) ---

Geom Title=D142-00-00 June 2007
Version=Version 3.0.1  Mar 2001

River Reach=D142-00-00      ,D142-00-00_0001
Reach XY= 30
      3064116.79    13825053.548     3064144.103    13824746.101
     3064173.475    13824563.217      3064218.29    13824416.909
     3064317.147    13824179.652     3064477.945    13823929.002
     3064601.677    13823784.259     3064944.859    13823471.427
     3065038.241    13823354.699     3065178.315    13823121.242
     3065295.044     13822838.76     3065337.066    13822647.326
     3065351.073    13822474.568     3065390.761    13821578.094
     3065444.117     13821325.98     3065505.155    13821146.199
     3065689.585    13820494.855     3065726.938    13820163.347
     3065750.284    13819537.683     3065733.942    13819360.256
     3065677.913    13819098.785     3064956.532    13816831.921
     3064912.175    13816684.843     3064865.483    13816474.732
     3064851.476    13816304.309     3064863.149    13815790.705
     3064944.859    13814032.776     3064928.743    13813996.062
     3064899.745    13813974.972     3064128.812    13813539.354

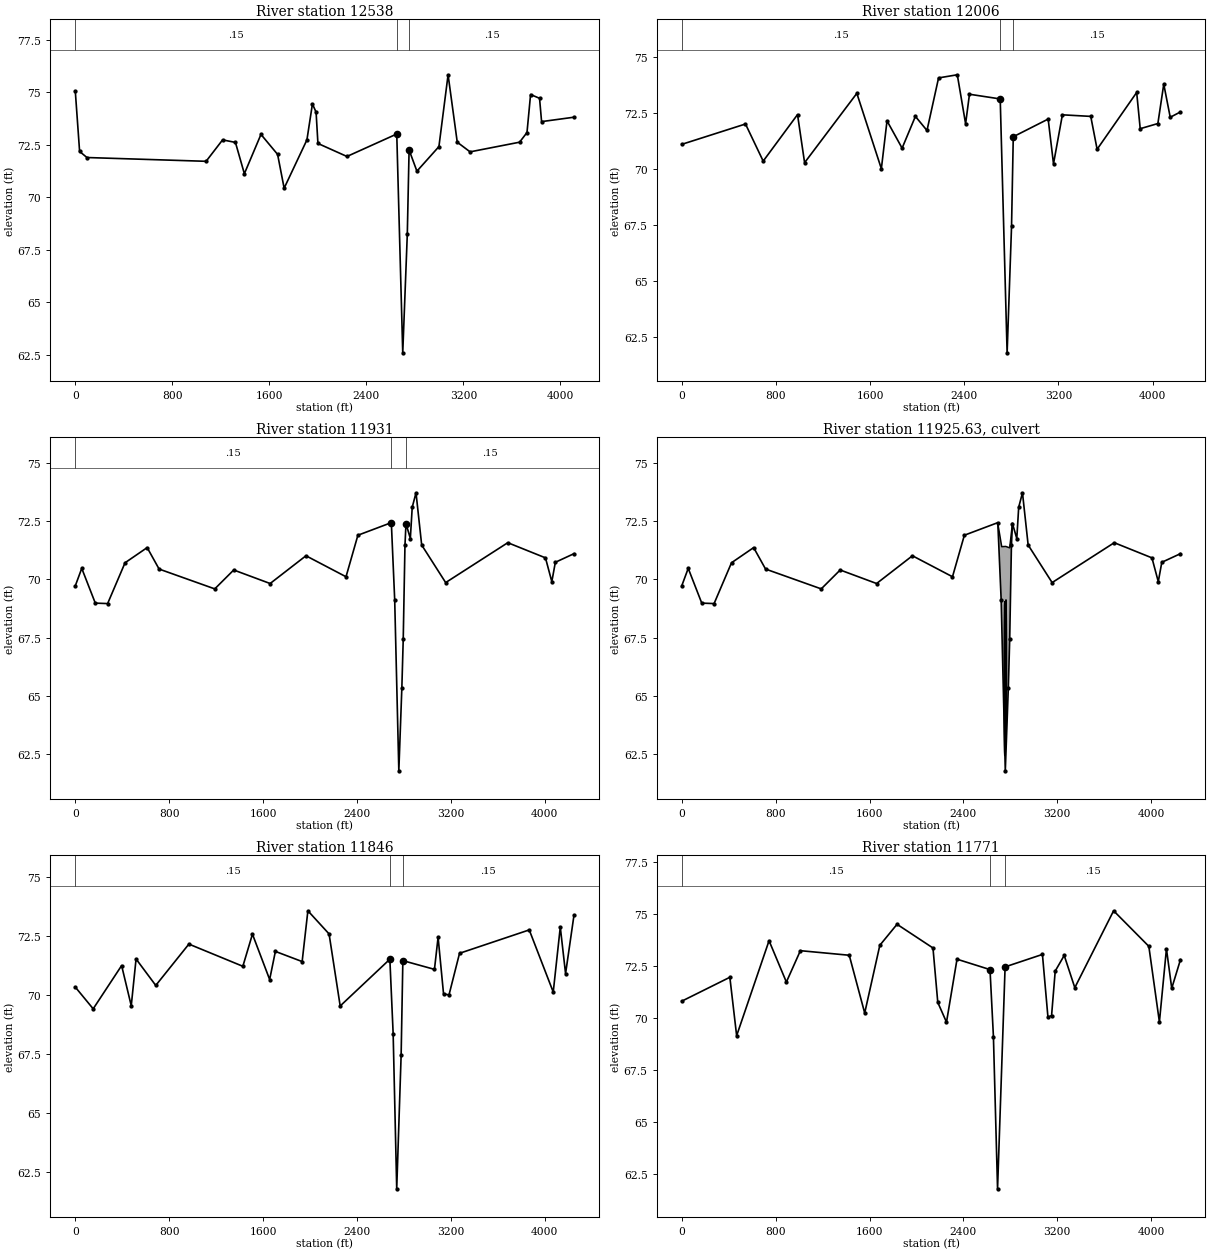
Type RM Length L Ch R = 1 ,12538   ,473.19,532.18,593.32
BEGIN DESCRIPTION:
Added Cross Section to Meet LODS
END DESCRIPTION:
XS GIS Cut Line= 2
       3066807.8    13825351.392     3062727.113    13824844.033
#Sta/Elev= 30
       0   75.05   35.58   72.18   96.04   71.89 1078.55   71.71 1214.58   72.73
 1320.39   72.61 1394.07   71.12 1530.96   72.99 1668.05   72.04 1722.04   70.43
  1909.9   72.73 1955.24   74.44 1985.47   74.05 2000.59   72.56 2239.89   71.94
 2650.56   73.01 2699.97   62.59 2737.53   68.24 2752.26   72.25 2816.83   71.24
 2998.21   72.41 3073.79   75.83 3149.37   72.62 3255.18   72.16 3663.29   72.62
 3724.39   73.08 3753.99   74.89 3827.96   74.71 3844.68    73.6 4112.11   73.81
#Mann= 3 , 0 , 0
       0     .15       0 2650.56     .04       0 2752.26     .15       0
#XS Ineff= 2 , 0
       0    2550            3052       0
Permanent Ineff=
       F       F
Bank Sta=2650.56,2752.26
XS Rating Curve= 0
Exp/Cntr=.3,.1

Type RM Length L Ch R = 1 ,12006   ,91.17,75,96.73
BEGIN DESCRIPTION:
Copied channel data from section 11930 of the original D142 model.
END DESCRIPTION:
XS GIS Cut Line= 6
       3066839.1     13824888.05     3065989.234     13825051.67
     3065723.104     13825051.67     3065381.477     13824974.53
     3063899.959     13824397.01     3062740.471     13824365.41
#Sta/Elev= 30
       0   71.11  541.44   72.02  691.84   70.36  983.52   72.44 1043.52   70.29
 1487.39   73.39 1695.65   70.02 1743.71   72.16 1871.87   70.94  1984.8   72.36
 2083.22   71.73 2181.65   74.08 2340.75   74.22  2411.3   72.03  2444.1   73.35
 2705.37   73.14 2763.97   61.79 2801.53   67.44 2816.26   71.45 3112.66   72.24
 3158.01   70.24  3233.6   72.43 3474.46   72.36 3528.55   70.89  3864.6   73.43
 3894.61   71.81 4044.64   72.04 4094.67    73.8 4149.66   72.32 4236.71   72.56
#Mann= 3 , 0 , 0
       0     .15       0 2705.37     .04       0 2816.26     .15       0
#XS Ineff= 2 , 0
       0    2330            3015       0
Permanent Ineff=
       T       T
Bank Sta=2705.37,2816.26
XS Rating Curve= 0
Exp/Cntr=.5,.3

Type RM Length L Ch R = 1 ,11931   ,100.85,85.01,92.25
BEGIN DESCRIPTION:
Copied channel data from section 11930 of the original D142 model.
END DESCRIPTION:
XS GIS Cut Line= 6
      3066852.86      13824785.6     3066558.101     13824795.77
     3065845.332     13824972.33     3065429.863     13824912.97
     3063741.972     13824261.08     3062758.501     13824264.91
#Sta/Elev= 30
       0   69.72    55.1   70.47  170.46   68.98  275.52   68.96  424.01   70.71
  612.53   71.36  714.18   70.44 1188.53   69.59    1350    70.4  1660.3   69.82
  1965.7   71.01 2306.99   70.11 2408.17   71.89 2693.13   72.43 2721.75   69.12
 2756.97   61.79 2782.73   65.35 2794.53   67.44 2809.26   71.45 2817.88   72.39
 2855.04   71.75 2871.16   73.09  2903.4   73.71 2951.76   71.47 3156.08   69.86
 3685.46   71.57 4006.59   70.92 4060.68    69.9 4090.69   70.73 4249.79    71.1
#Mann= 3 , 0 , 0
       0     .15       0 2693.13     .04       0 2817.88     .15       0
#XS Ineff= 2 , 0
       0    2425            2915       0
Permanent Ineff=
       T       T
Bank Sta=2693.13,2817.88
XS Rating Curve= 0
Exp/Cntr=.5,.3

Type RM Length L Ch R = 2 ,11925.63,,,
BEGIN DESCRIPTION:
Harwin Culverts
END DESCRIPTION:
Bridge Culvert--1,0,-1,-1, 0
Deck Dist Width WeirC Skew NumUp NumDn MinLoCord MaxHiCord MaxSubmerge Is_Ogee
5,75,2.6,0, 5, 5, , , .95, 0, 0,0,,
 2693.08 2726.43 2760.43 2794.43 2817.89
    72.4    71.4   71.41   71.35    72.4
       0       0       0       0       0
 2680.54 2711.43 2745.43 2779.43 2791.26
   71.47    71.4   71.41   71.35   71.44
       0       0       0       0       0
BR Coef=-1 , 0 , 0 ,, 0 ,,,.8,-1,,0,
WSPro=,,,, 1 ,,,, 0 ,,,, 0 ,,,,-1 ,-1 ,-1 , 0 , 0 , 0 , 0 , 0
Culvert=5,6.625,10,75,.031,.9,1,41,1,62.425,2751.85,62.425,2736.85,Culvert #1  , 0 ,5
Culvert Bottom n=.031
Culvert=5,6.167,10,75,.031,.9,1,41,1,62.963,2762.85,62.963,2747.85,Culvert #2  , 0 ,5
Culvert Bottom n=.031
BC Design=,, 0 ,, 0 ,,,,,,

Type RM Length L Ch R = 1 ,11846   ,85.09,75.02,75.21
BEGIN DESCRIPTION:
Copied channel data from section 11930 of the original D142 model.
END DESCRIPTION:
XS GIS Cut Line= 6
      3066849.93     13824700.65     3066540.595     13824711.32
     3065845.332     13824886.46     3065452.819     13824830.39
     3063755.954     13824176.88     3062755.582     13824179.97
#Sta/Elev= 30
       0   70.33  152.52   69.41  394.79   71.24  476.84   69.54  517.86   71.52
  685.68    70.4  967.97   72.15 1427.82   71.21 1509.61   72.57  1656.2   70.65
 1705.06   71.84  1933.1   71.41 1981.96   73.56 2162.58   72.58 2257.19   69.53
 2680.53   71.51 2708.53   68.36 2738.97   61.79 2776.53   67.44 2791.26   71.45
 3060.54   71.08 3091.54   72.44 3138.05   70.04 3184.55      70 3274.23   71.76
 3868.24   72.75 4072.72   70.12 4132.76   72.87 4177.78    70.9 4249.74   73.38
#Mann= 3 , 0 , 0
       0     .15       0 2680.53     .04       0 2791.26     .15       0
#XS Ineff= 2 , 0
       0    2200            2950       0
Permanent Ineff=
       T       T
Bank Sta=2680.53,2791.26
XS Rating Curve= 0
Exp/Cntr=.5,.3

Type RM Length L Ch R = 1 ,11771   ,1301.87,1317.23,1332.59
BEGIN DESCRIPTION:
Copied channel data from section 11930 of the original D142 model.
END DESCRIPTION:
XS GIS Cut Line= 6
      3066847.35      13824625.7     3066525.149     13824636.81
     3065845.332      13824810.7     3065473.074     13824757.52
     3063768.291     13824102.59     3062753.005     13824105.01
#Sta/Elev= 30
       0   70.82  409.82   71.97  467.67   69.16  743.81   73.73  891.51   71.74
 1010.84   73.25 1427.22   73.03 1558.88   70.25 1687.83   73.51 1834.42   74.52
 2140.69   73.38 2181.66   70.76 2255.92   69.81 2345.54   72.84 2626.66   72.34
 2655.75   69.12 2690.97   61.79 2755.25   72.47 3073.37   73.07 3120.32   70.05
 3151.32   70.13 3182.33   72.27 3259.04   73.02 3349.29   71.47 3679.88   75.17
 3980.06   73.46 4070.11   69.82 4130.15   73.34 4175.17   71.44 4249.71   72.82
#Mann= 3 , 0 , 0
       0     .15       0 2626.66     .04       0 2755.25     .15       0
#XS Ineff= 2 , 0
       0    2130            2890       0
Permanent Ineff=
       T       T
Bank Sta=2626.66,2755.25
XS Rating Curve= 0
Exp/Cntr=.3,.1

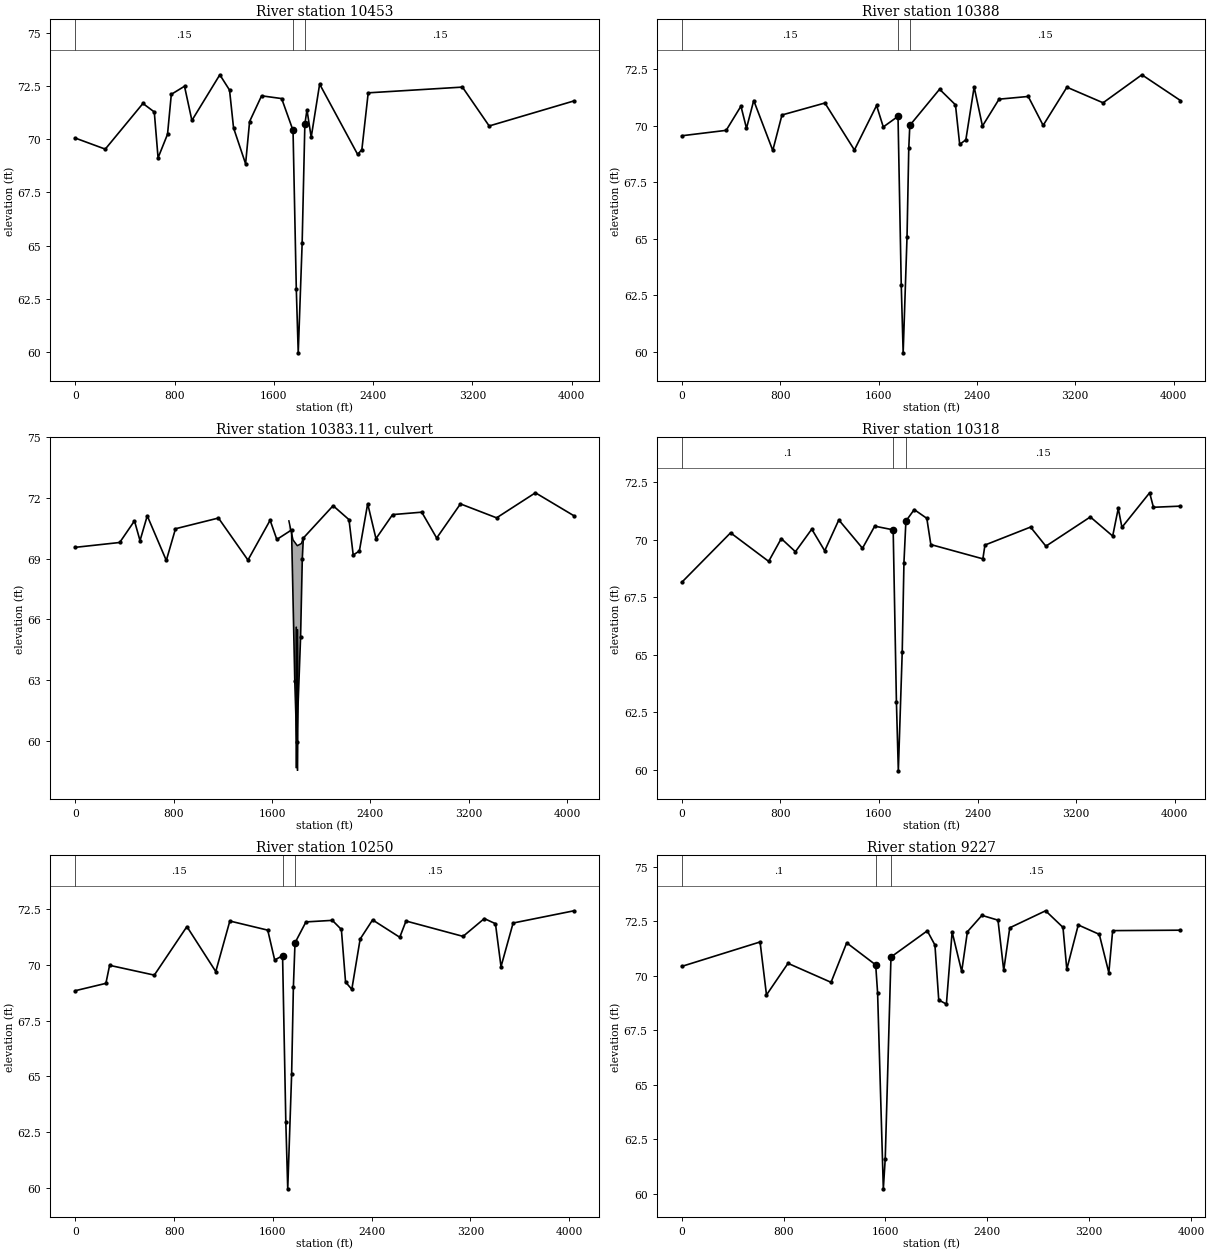
Type RM Length L Ch R = 1 ,10453   ,67.57,65.18,63.81
BEGIN DESCRIPTION:
Copied channel data from section 10250 of the original D142 model.
END DESCRIPTION:
XS GIS Cut Line= 6
      3066848.55     13823384.66     3066030.525       13823498.
     3065659.363     13823491.37     3064187.974      13822762.3
     3063762.565     13822632.24     3063031.961     13822588.62
#Sta/Elev= 30
       0   70.06  241.54   69.54  545.07   71.69  636.53   71.29  667.01   69.13
  743.22   70.24   773.7   72.12  880.01    72.5  939.56   70.89  1164.6   73.04
 1242.87   72.32 1275.22   70.54 1372.25   68.85 1404.59   70.84 1501.11   72.05
 1662.91   71.92 1754.55   70.42 1780.88   62.95  1796.4   59.95 1827.91    65.1
 1849.83   70.72 1866.85   71.39 1900.88    70.1 1968.94    72.6 2275.21   69.29
 2309.24   69.52 2360.29   72.19 3119.45   72.46 3334.98   70.63  4018.6   71.81
#Mann= 3 , 0 , 0
       0     .15       0 1754.55     .04       0 1849.83     .15       0
#XS Ineff= 2 , 0
       0    1234            2354       0
Permanent Ineff=
       T       T
Bank Sta=1754.55,1849.83
XS Rating Curve= 0
Exp/Cntr=.5,.3

Type RM Length L Ch R = 1 ,10388   ,70.01,70.06,70
BEGIN DESCRIPTION:
Copied channel data from section 10250 of the original D142 model.
END DESCRIPTION:
XS GIS Cut Line= 6
      3066877.99     13823340.03     3065942.116     13823449.47
     3065663.895     13823441.74     3064214.997     13822720.52
     3063739.434     13822575.79     3063024.209     13822533.09
#Sta/Elev= 30
       0   69.56  361.11    69.8  481.32   70.87   526.4   69.89   585.2   71.12
  740.12   68.91  814.84   70.48 1164.12   71.01    1404   68.93 1584.18    70.9
 1638.82   69.95 1758.55   70.42 1784.88   62.95  1800.4   59.95 1831.91    65.1
 1846.02      69 1854.48   70.02 2096.52   71.62 2225.69   70.93 2259.99   69.18
  2310.1   69.38 2377.63   71.72 2445.15   69.99 2580.21   71.18 2817.39    71.3
 2938.76   70.02 3131.94   71.71 3426.07   71.02 3741.63   72.26 4055.48   71.12
#Mann= 3 , 0 , 0
       0     .15       0 1758.55     .04       0 1854.48     .15       0
#XS Ineff= 2 , 0
       0    1207            2353       0
Permanent Ineff=
       T       T
Bank Sta=1758.55,1854.48
XS Rating Curve= 0
Exp/Cntr=.5,.3

Type RM Length L Ch R = 2 ,10383.11,,,
BEGIN DESCRIPTION:
Townpark Culverts
END DESCRIPTION:
Bridge Culvert--1,0,-1,-1, 0
Deck Dist Width WeirC Skew NumUp NumDn MinLoCord MaxHiCord MaxSubmerge Is_Ogee
5,60,2.6,0, 5, 5, , , .95, 0, 0,0,,
  1736.9 1770.46 1805.46 1838.46 1854.49
   70.87   69.93   69.64   69.75   70.03
       0       0       0       0       0
 1715.54 1726.04 1761.04 1794.04 1818.82
   70.42   69.93   69.64   69.75    70.8
       0       0       0       0       0
Culvert=1,7,,60,.031,.7,1,2,2,58.63,1797.69,58.63,1753.27,Culvert #1  , 0 ,5
Culvert Bottom n=.031
Culvert=1,7,,60,.031,.7,1,2,2,58.5,1806.99,58.5,1762.57,Culvert #2  , 0 ,5
Culvert Bottom n=.031
BC Design=,, 0 ,, 0 ,,,,,,

Type RM Length L Ch R = 1 ,10318   ,68.01,68.06,68
BEGIN DESCRIPTION:
Copied channel data from section 10250 of the original D142 model.
END DESCRIPTION:
XS GIS Cut Line= 6
      3066873.88     13823270.15     3065936.191     13823379.28
     3065679.291     13823372.14     3064241.463     13822655.41
     3063751.882      13822506.4     3063028.381     13822463.21
#Sta/Elev= 30
       0   68.14  396.15   70.29  705.26   69.05  807.48   70.04   922.3   69.47
 1054.92   70.45 1159.96   69.51 1274.41   70.85 1466.56   69.62 1565.59   70.58
 1715.55   70.42 1741.88   62.95  1757.4   59.95 1788.91    65.1 1803.02      69
 1818.82    70.8 1886.34    71.3 1988.49   70.92 2021.18   69.78 2443.44   69.16
 2460.32   69.76  2830.2   70.54 2954.71   69.71 3315.34   70.98 3496.82   70.15
 3541.91   71.35 3571.96   70.53 3796.74   72.03 3827.41    71.4 4046.92   71.45
#Mann= 3 , 0 , 0
       0      .1       0 1715.55     .04       0 1818.82     .15       0
#XS Ineff= 2 , 0
       0    1136            2309       0
Permanent Ineff=
       T       T
Bank Sta=1715.55,1818.82
XS Rating Curve= 0
Exp/Cntr=.5,.3

Type RM Length L Ch R = 1 ,10250   ,1081.68,1022.69,972.61
BEGIN DESCRIPTION:
Copied channel data from section 10250 of the original D142 model.
END DESCRIPTION:
XS GIS Cut Line= 6
      3066869.89     13823202.27     3065930.435     13823311.09
     3065694.247     13823304.53     3064267.172     13822592.15
     3063763.975     13822439.01     3063032.434     13822395.33
#Sta/Elev= 30
       0   68.85  247.82   69.18  277.87   69.99  639.93   69.55  903.84   71.73
 1137.59   69.71 1251.44   71.98 1558.47   71.57 1614.58   70.23 1678.55   70.42
 1704.88   62.95  1720.4   59.95 1751.91    65.1 1766.02      69  1779.2      71
 1867.81   71.94 2081.57   72.01 2154.79    71.6 2188.56   69.24  2239.2   68.91
 2306.73   71.17 2407.51   72.03 2627.48   71.25 2678.13   71.98 3140.07   71.29
 3312.26   72.09 3402.42   71.86  3447.5   69.93 3545.45   71.89 4038.61   72.44
#Mann= 3 , 0 , 0
       0     .15       0 1678.55     .04       0  1779.2     .15       0
#XS Ineff= 2 , 0
       0    1102            2278       0
Permanent Ineff=
       T       T
Bank Sta=1678.55,1779.2
XS Rating Curve= 0
Exp/Cntr=.3,.1

Type RM Length L Ch R = 1 ,9227    ,1075.81,1091.42,1103.06
XS GIS Cut Line= 4
      3066927.23     13822390.21     3065553.261     13822084.89
     3065237.029     13822073.98     3063045.217     13821986.75
#Sta/Elev= 30
       0   70.42   615.1   71.54  665.58   69.11   834.6   70.56 1172.65   69.69
 1295.58    71.5 1523.31   70.49 1538.32   69.21 1583.35   60.22 1598.36   61.61
 1643.39   70.85  1928.6   72.05 1988.64    71.4 2018.67   68.88 2078.71   68.69
 2123.75      72 2198.81   70.19 2243.84   72.01 2357.66   72.76 2484.03   72.54
 2529.07   70.24 2576.53   72.19 2857.95   72.97 2994.44   72.21 3024.46   70.29
 3114.53   72.32 3279.66   71.89 3354.72   70.13 3384.74   72.06 3917.45   72.08
#Mann= 3 , 0 , 0
       0      .1       0 1523.31     .04       0 1643.39     .15       0
#XS Ineff= 2 , 0
       0     863            2113       0
Permanent Ineff=
       T       T
Bank Sta=1523.31,1643.39
XS Rating Curve= 0
Exp/Cntr=.3,.1

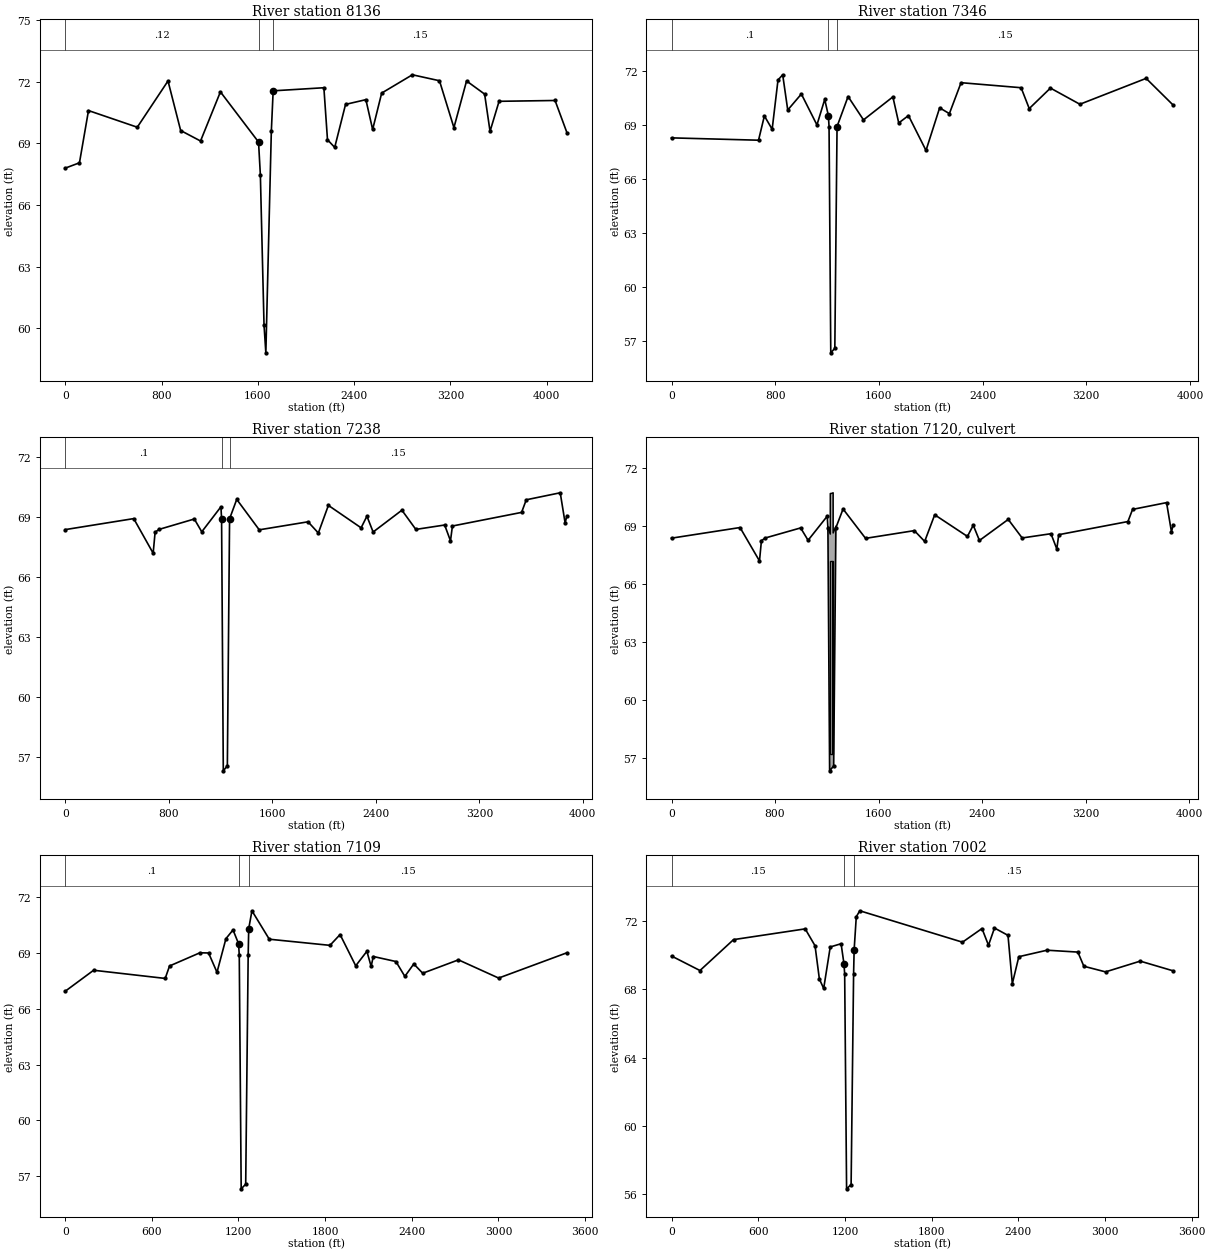
Type RM Length L Ch R = 1 ,8136    ,802.05,789.95,766.15
XS GIS Cut Line= 4
     3067205.906    13821095.787     3065729.233     13821039.53
     3065380.288     13820985.01     3063044.162    13820945.445
#Sta/Elev= 30
       0   67.79  118.49   68.05  193.55   70.59  598.84   69.78  854.03   72.03
   959.1   69.62 1124.22   69.11 1289.34    71.5 1606.01   69.06  1621.2   67.46
 1651.56   60.17 1666.74   58.81 1712.29   69.58 1727.47   71.55 2148.76    71.7
 2178.76   69.17 2238.77    68.8 2328.78   70.89 2497.59   71.12 2553.81   69.67
 2628.83   71.44 2883.86   72.33 3108.89   72.04 3228.91   69.76 3333.93   72.03
 3483.95   71.39 3528.95   69.58 3603.96   71.04 4069.03   71.08 4167.38   69.52
#Mann= 3 , 0 , 0
       0     .12       0 1606.01     .04       0 1727.47     .15       0
#XS Ineff= 2 , 0
       0     953            2262       0
Permanent Ineff=
       T       T
Bank Sta=1606.01,1727.47
XS Rating Curve= 0
Exp/Cntr=.3,.1

Type RM Length L Ch R = 1 ,7346    ,109.17,108.54,115.5
XS GIS Cut Line= 4
      3066962.96    13820312.051     3065744.844     13820247.06
     3065674.359    13820246.826     3063098.802    13820408.687
#Sta/Elev= 30
       0   68.28  671.41   68.15  716.48    69.5  776.56   68.76  821.63    71.5
  857.83   71.79  896.73   69.83 1001.88   70.72 1122.05      69 1182.14   70.42
 1210.52   69.51 1215.45   68.91 1228.75   56.32 1260.05   56.57 1277.23   68.91
 1362.33   70.58 1481.27   69.28 1708.02   70.56  1753.1   69.11 1828.25   69.52
 1963.52   67.58 2068.73   69.95 2143.87   69.63 2234.05   71.35 2697.39   71.07
 2760.09   69.91 2923.64   71.05 3150.86   70.15 3661.86   71.59 3870.97    70.1
#Mann= 3 , 0 , 0
       0      .1       0 1210.52     .04       0 1277.23     .15       0
#XS Ineff= 2 , 0
       0     837            1943       0
Permanent Ineff=
       T       T
Bank Sta=1210.52,1277.23
XS Rating Curve= 0
Exp/Cntr=.5,.3

Type RM Length L Ch R = 1 ,7238    ,127.59,128.02,126.77
XS GIS Cut Line= 4
     3066971.322    13820203.202     3065772.504     13820139.24
     3065702.019    13820139.006     3063098.802    13820022.993
#Sta/Elev= 30
       0   68.37  529.57   68.92  679.79   67.19  694.81   68.24  724.85   68.38
  997.69    68.9 1055.32   68.26 1203.52   69.51 1208.45   68.91 1221.75   56.32
 1253.05   56.57 1270.23   68.91 1325.58   69.88 1499.42   68.36 1876.58   68.76
 1956.21    68.2 2033.74   69.58 2286.53   68.46 2331.58   69.04 2379.47   68.25
 2601.85   69.34 2709.49   68.38 2932.17    68.6 2977.22   67.81 2992.23   68.55
 3526.68   69.23  3562.8   69.86 3825.27   70.21  3863.1    68.7 3876.81   69.06
#Mann= 3 , 0 , 0
       0      .1       0 1208.45     .04       0 1270.23     .15       0
#XS Ineff= 2 , 0
       0     903            1867       0
Permanent Ineff=
       T       T
Bank Sta=1208.45,1270.23
XS Rating Curve= 0
Exp/Cntr=.5,.3

Type RM Length L Ch R = 2 ,7120    ,,,
BEGIN DESCRIPTION:
Bellaire Culvert
END DESCRIPTION:
Bridge Culvert--1,0,-1,-1, 0
Deck Dist Width WeirC Skew NumUp NumDn MinLoCord MaxHiCord MaxSubmerge Is_Ogee
5.6,110,2.6,0, 7, 7, , , .95, 0, 0,0,,
 1208.45 1226.77 1226.87 1237.97 1249.07 1249.17 1270.24
   68.92   68.58   70.68   70.69   70.72   68.64   68.98
       0       0       0       0       0       0       0
 1205.36  1223.9    1224  1235.1  1246.2  1246.3 1267.25
   68.92   68.58   70.68   70.69   70.72   68.64   68.92
       0       0       0       0       0       0       0
Multiple Barrel Culv=2,10,10,110,.015,.4,1,8,1,57.2,56.9, 2,Culvert #1  , 0 ,5.6
 1232.72 1229.85 1243.22 1240.35
Culvert Bottom n=.015
BC Design=,, 0 ,, 0 ,,,,,,

Type RM Length L Ch R = 1 ,7109    ,106.53,107.91,106.01
BEGIN DESCRIPTION:
Survey
END DESCRIPTION:
XS GIS Cut Line= 4
     3066969.088    13820075.325      3065770.27    13820011.364
     3065699.785    13820011.129     3063497.353    13819945.854
#Sta/Elev= 30
       0   66.95  196.87   68.08  692.57   67.64  722.61   68.31  932.91   69.02
     993   69.01 1051.27   67.97 1113.17   69.78 1162.34   70.25 1200.52   69.51
 1205.45   68.91 1218.75   56.32 1250.05   56.57 1267.23   68.91 1271.01   70.32
  1293.3   71.28 1413.36   69.75 1833.54   69.42 1903.68      70 2011.94   68.32
 2089.26    69.1 2118.67   68.29 2133.67   68.82 2290.31   68.55 2352.17   67.75
 2414.03   68.42 2475.89   67.92 2723.33   68.64  3001.7   67.66 3474.41   69.02
#Mann= 3 , 0 , 0
       0      .1       0 1200.52    .015       0 1271.01     .15       0
#XS Ineff= 2 , 0
       0     971            1807       0
Permanent Ineff=
       T       T
Bank Sta=1200.52,1271.01
XS Rating Curve= 0
Exp/Cntr=.5,.3

Type RM Length L Ch R = 1 ,7002    ,16.9,16.76,20.66
XS GIS Cut Line= 4
     3066969.074    13819976.585     3065768.529      13819903.7
     3065702.723    13819902.725     3063499.018    13819933.029
#Sta/Elev= 30
       0   69.96  196.94   69.11  429.29   70.92  925.26   71.55   993.4   70.56
 1023.45   68.61 1053.25   68.06 1098.59   70.49 1173.73   70.68 1193.52   69.51
 1198.45   68.91 1211.75   56.32 1243.05   56.57 1260.23   68.91 1264.01   70.32
 1278.79   72.26 1303.09   72.61 2013.86   70.77 2148.87   71.57 2193.88   70.59
 2235.36    71.6 2328.89   71.17 2358.89   68.34  2403.9   69.92 2598.92    70.3
 2812.48   70.19 2853.94   69.36 3003.96   69.03 3243.98   69.66 3472.48   69.09
#Mann= 3 , 0 , 0
       0     .15       0 1193.52    .015       0 1264.01     .15       0
#XS Ineff= 2 , 0
       0    1017            1740       0
Permanent Ineff=
       T       T
Bank Sta=1193.52,1264.01
XS Rating Curve= 0
Exp/Cntr=.3,.1

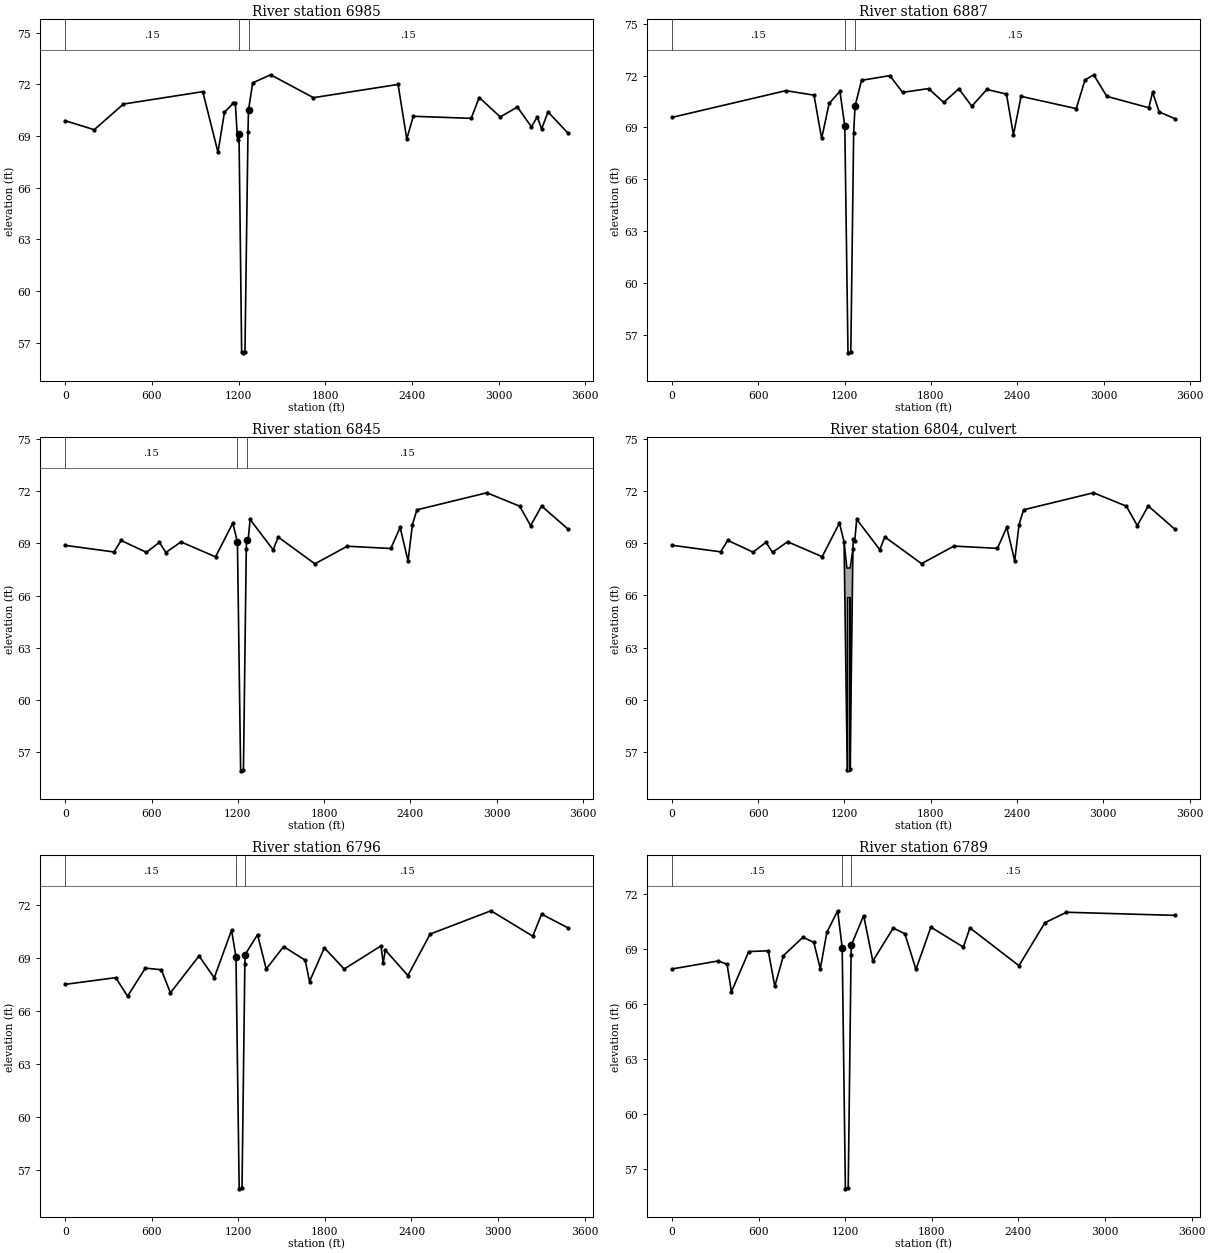
Type RM Length L Ch R = 1 ,6985    ,97.51,97.45,97.59
BEGIN DESCRIPTION:
Survey
END DESCRIPTION:
XS GIS Cut Line= 5
     3066972.717     13819959.88     3065772.172    13819886.995
     3065706.366     13819886.02     3064648.008    13819833.359
     3063499.591     13819928.44
#Sta/Elev= 30
       0   69.89  200.59   69.37     403   70.86  951.97   71.58 1057.16   68.06
 1102.24   70.39 1162.35    70.9 1177.38   70.91 1192.41   68.77 1202.76   69.13
    1221   56.45 1232.43   56.41 1243.86   56.44 1264.81   69.25 1268.57   70.52
 1297.47   72.09 1421.71   72.56 1717.99   71.23 2303.71      72 2363.86   68.83
 2409.02   70.15 2809.79   70.03 2865.39   71.24 3011.07   70.11  3129.5   70.69
 3226.81   69.54 3266.94   70.12 3297.05   69.42  3342.2    70.4 3480.58   69.16
#Mann= 3 , 0 , 0
       0     .15       0 1202.76    .015       0 1268.57     .15       0
#XS Ineff= 2 , 0
       0    1021            1705       0
Permanent Ineff=
       T       T
Bank Sta=1202.76,1268.57
XS Rating Curve= 0
Exp/Cntr=.3,.1

Type RM Length L Ch R = 1 ,6887    ,43.67,42.01,42.24
XS GIS Cut Line= 5
     3066978.069    13819862.515     3065777.524     13819789.63
     3065711.718    13819788.655     3064744.431     13819740.15
     3063500.165    13819919.264
#Sta/Elev= 30
       0   69.58  792.02   71.13  987.38   70.87 1040.52   68.36 1092.58   70.39
 1167.71   71.09 1201.45   69.08  1223.7   55.94 1243.25   55.99 1263.04   68.69
 1272.79   70.24 1317.85   71.73 1514.24      72 1603.21   71.03 1783.43   71.25
 1888.56   70.45  1993.7   71.24 2083.81   70.23 2188.94    71.2  2324.9   70.93
 2373.33   68.57 2426.32    70.8 2809.85   70.09 2870.47   71.75 2931.08   72.05
 3022.01    70.8 3313.91   70.14  3340.4   71.04 3385.72    69.9 3494.16   69.51
#Mann= 3 , 0 , 0
       0     .15       0 1201.45    .015       0 1272.79     .15       0
#XS Ineff= 2 , 0
       0    1025            1617       0
Permanent Ineff=
       T       T
Bank Sta=1201.45,1272.79
XS Rating Curve= 0
Exp/Cntr=.5,.3

Type RM Length L Ch R = 1 ,6845    ,49.01,49.05,48.08
XS GIS Cut Line= 5
     3066976.343     13819807.89     3065785.805     13819747.55
      3065721.86    13819747.112     3064747.646    13819695.152
     3063500.739    13819911.234
#Sta/Elev= 30
       0   68.89  339.28   68.51  388.62   69.17  564.57   68.49  654.68   69.06
  699.74   68.48  804.87   69.09 1045.18   68.23 1165.34   70.17 1197.45   69.08
  1219.7   55.94 1239.25   55.99 1259.04   68.69  1261.4   69.22 1271.61   69.14
 1285.41   70.38 1446.16   68.63 1480.69   69.37 1736.05   67.83 1961.37   68.84
 2264.04   68.71 2328.92   69.92 2383.99   67.99 2414.44   70.08 2445.69   70.93
 2932.04   71.91 3160.39   71.14 3236.51   70.02 3312.63   71.15  3497.1   69.82
#Mann= 3 , 0 , 0
       0     .15       0 1197.45    .015       0  1261.4     .15       0
#XS Ineff= 2 , 0
       0    1022            1573       0
Permanent Ineff=
       T       T
Bank Sta=1197.45,1261.4
XS Rating Curve= 0
Exp/Cntr=.5,.3

Type RM Length L Ch R = 2 ,6804    ,,,
BEGIN DESCRIPTION:
Leader Box Culverts
END DESCRIPTION:
Bridge Culvert--1,0,-1,-1, 0
Deck Dist Width WeirC Skew NumUp NumDn MinLoCord MaxHiCord MaxSubmerge Is_Ogee
5,40,2.6,0, 5, 5, , , .95, 0, 0,0,,
 1197.45 1217.34 1228.34 1238.84 1259.04
   69.12   67.57   67.58   67.57   68.67
       0       0       0       0       0
 1183.47  1203.5  1214.5    1225  1245.1
    69.1   67.57   67.58   67.57   68.68
       0       0       0       0       0
Multiple Barrel Culv=2,10,10,40,.015,.5,1,8,2,55.9,55.9, 2,Culvert #1  , 0 ,5
 1224.09 1210.25 1234.59 1220.75
Culvert Bottom n=.015
BC Design=,, 0 ,, 0 ,,,,,,

Type RM Length L Ch R = 1 ,6796    ,7.14,7.18,7.31
XS GIS Cut Line= 5
     3066963.977    13819756.897     3065782.372    13819698.524
     3065718.427    13819698.086     3064738.003    13819656.583
     3063501.886    13819887.145
#Sta/Elev= 30
       0   67.53  349.76   67.91     432   66.86  555.15   68.45  665.74   68.36
  728.93   67.05  927.61   69.14 1032.73    67.9 1152.88    70.6 1183.45   69.08
  1205.7   55.94 1225.25   55.99 1245.04   68.69  1247.4   69.22    1333   70.35
 1393.05    68.4 1513.86   69.67 1663.29    68.9 1693.32   67.69 1796.05    69.6
 1933.53    68.4 2188.76   69.71 2203.78   68.75 2218.79   69.47 2375.26   68.03
 2529.58   70.38 2951.05    71.7 3240.96   70.26 3301.99   71.51 3485.72   70.73
#Mann= 3 , 0 , 0
       0     .15       0 1183.45    .015       0  1247.4     .15       0
#XS Ineff= 2 , 0
       0    1010            1517       0
Permanent Ineff=
       T       T
Bank Sta=1183.45,1247.4
XS Rating Curve= 0
Exp/Cntr=.5,.3

Type RM Length L Ch R = 1 ,6789    ,444.75,422.93,392.71
BEGIN DESCRIPTION:
Survey
END DESCRIPTION:
XS GIS Cut Line= 5
     3066959.321    13819749.538     3065781.303    13819691.342
     3065717.357    13819690.904     3064741.932    13819646.868
     3063500.739    13819881.409
#Sta/Elev= 30
       0   67.91  322.21   68.35  382.29   68.16  412.32   66.67  532.47   68.86
  667.63    68.9  712.69   66.97  772.76   68.64  907.93   69.64  983.02   69.36
 1028.07   67.92 1073.13    69.9 1148.22   71.08 1179.45   69.08  1201.7   55.94
 1221.25   55.99 1241.04   68.69  1243.4   69.22 1328.35   70.82 1391.69   68.34
 1533.22   70.14 1613.64   69.83 1690.47   67.89 1793.82   70.19 2019.05    69.1
 2064.09   70.15 2403.91   68.09 2583.66   70.43 2733.18      71 3482.98   70.83
#Mann= 3 , 0 , 0
       0     .15       0 1179.45    .015       0  1243.4     .15       0
#XS Ineff= 2 , 0
       0    1005            1505       0
Permanent Ineff=
       T       T
Bank Sta=1179.45,1243.4
XS Rating Curve= 0
Exp/Cntr=.3,.1