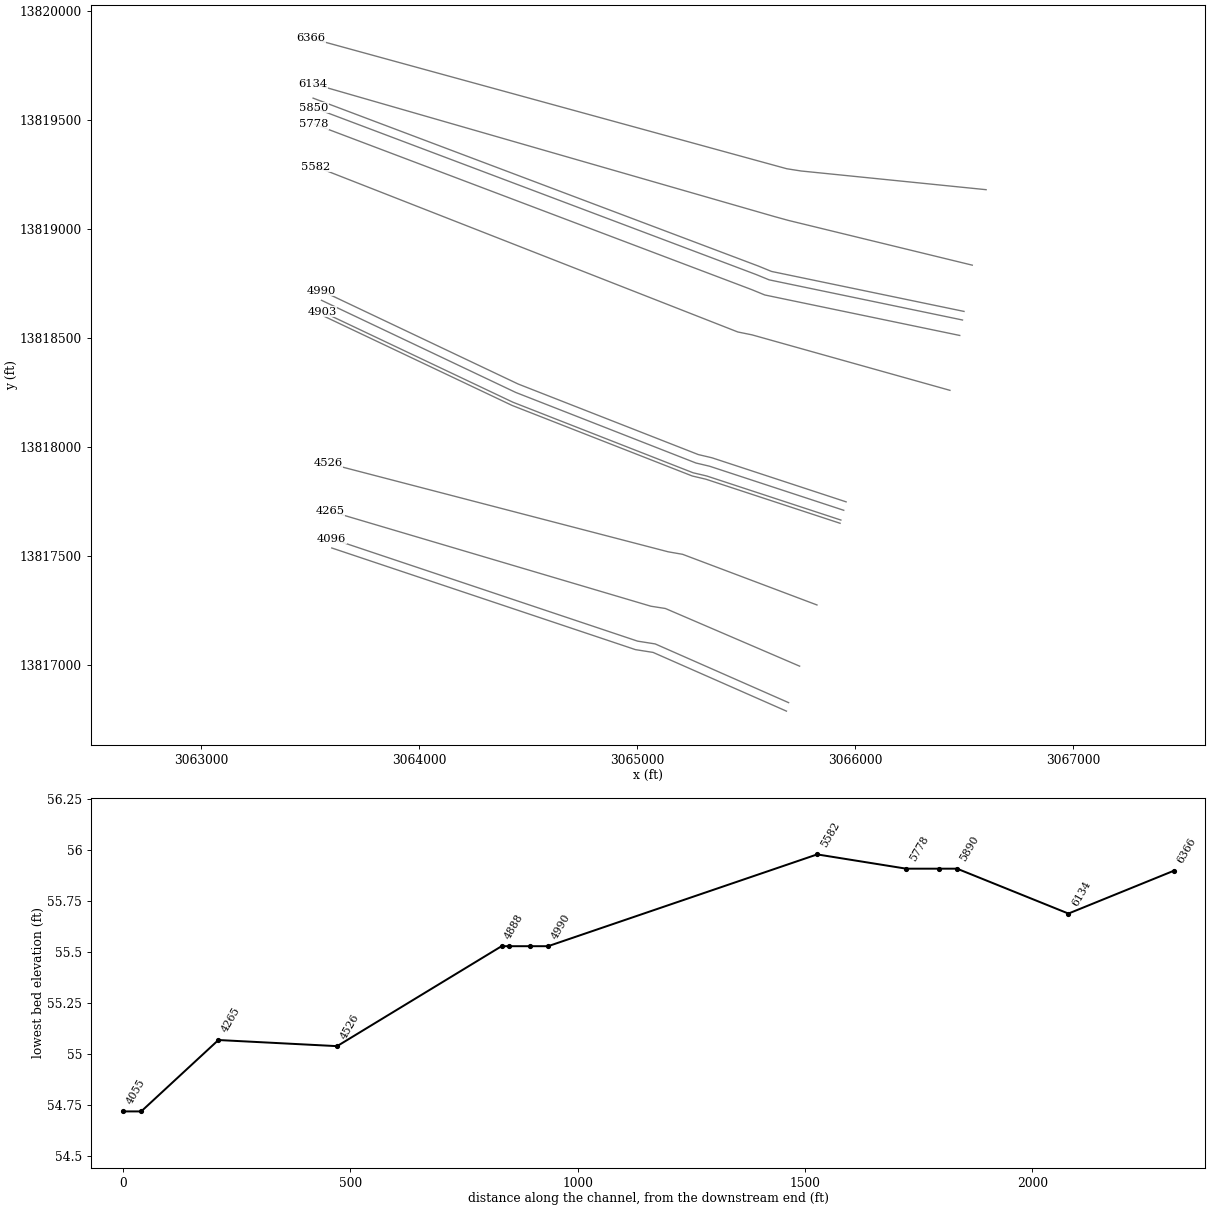
HEC-RAS study D142-00-00.prj: D142-00-00

--- D142-00-00.g03 (geometry) --- (continued)

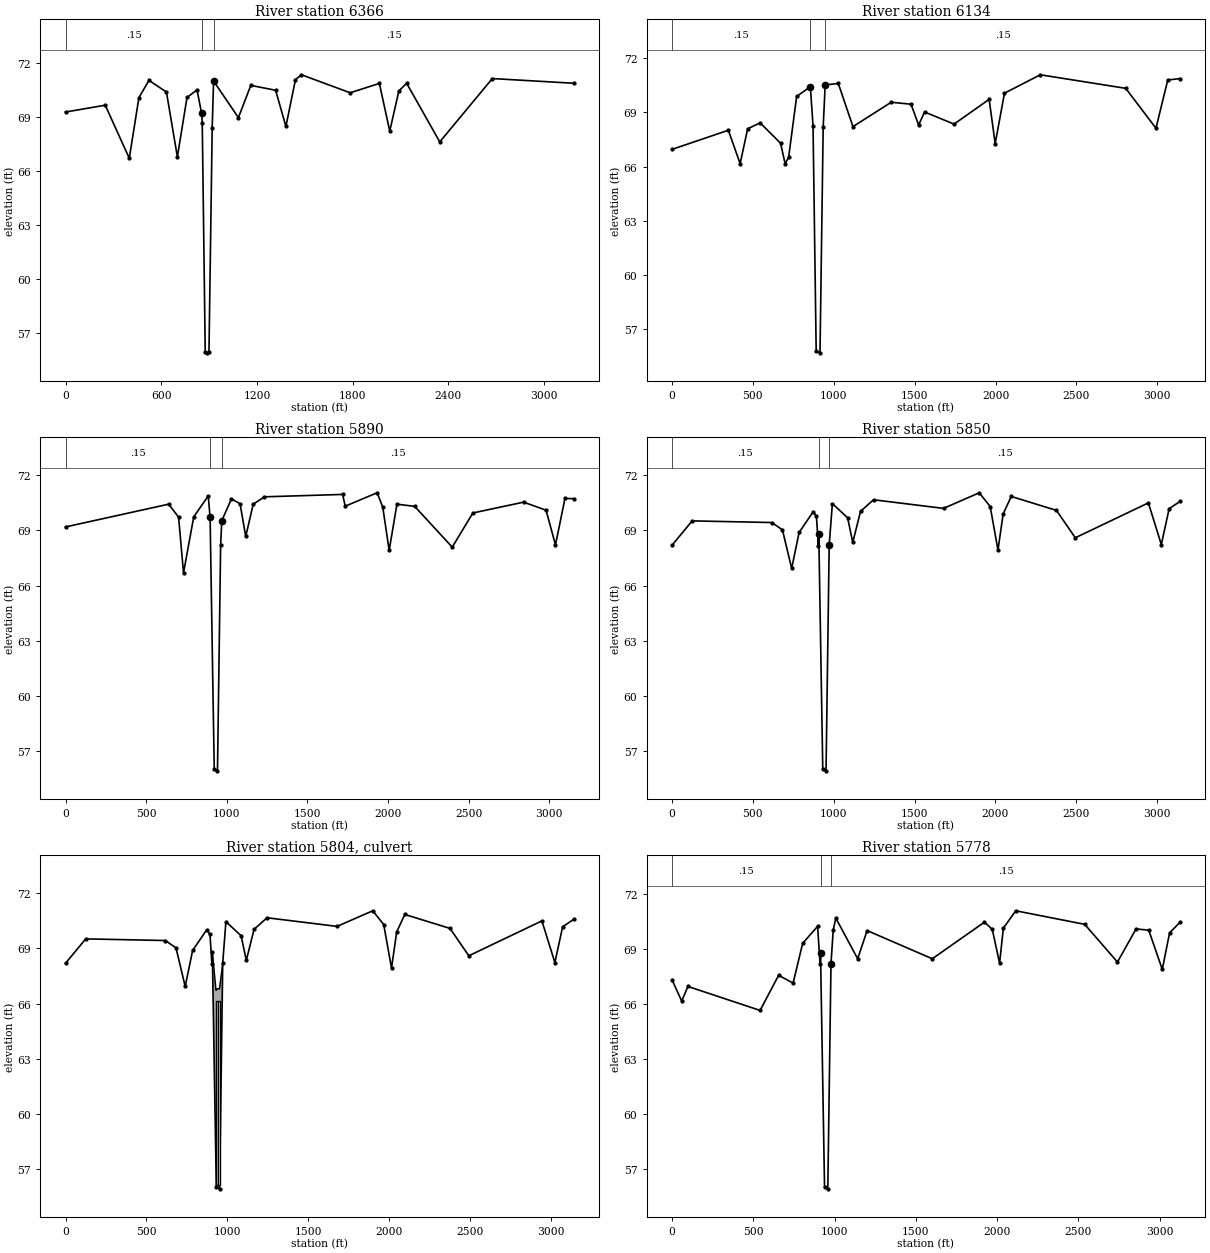
Type RM Length L Ch R = 1 ,6366    ,247.82,231.9,225.79
BEGIN DESCRIPTION:
Survey
END DESCRIPTION:
XS GIS Cut Line= 4
     3066600.329    13819182.141     3065751.306    13819267.898
     3065685.894    13819278.173     3063501.238    13819876.777
#Sta/Elev= 30
       0   69.28  249.09   69.66  399.85   66.71  460.16   70.08  523.25   71.04
   632.8   70.39  701.26   66.79  761.69   70.09   824.5   70.51  853.34    69.2
  857.17   68.68  875.89   55.95  887.65    55.9  899.34   55.95  919.56   68.41
  928.26      71 1083.79   68.97 1161.55   70.76 1317.08   70.49  1381.6   68.48
 1441.51   71.08 1479.27   71.35 1784.46   70.35 1967.58   70.87 2032.52   68.22
 2089.66   70.45 2138.49   70.88 2346.03   67.62 2675.64   71.14 3184.74   70.88
#Mann= 3 , 0 , 0
       0     .15       0  853.34    .015       0  928.26     .15       0
#XS Ineff= 2 , 0
       0     668            1106       0
Permanent Ineff=
       T       T
Bank Sta=853.34,928.26
XS Rating Curve= 0
Exp/Cntr=.3,.1

Type RM Length L Ch R = 1 ,6134    ,242.95,244.77,233.01
BEGIN DESCRIPTION:
Survey
END DESCRIPTION:
XS GIS Cut Line= 4
     3066536.927    13818835.954     3065693.705    13819041.083
     3065629.292    13819058.813     3063509.878    13819668.727
#Sta/Elev= 30
       0   66.95  348.48   68.01  421.37   66.16  467.68   68.09  544.87   68.42
  671.31   67.29  699.24   66.16  720.98   66.51  770.65   69.88  855.26   70.42
  871.86   68.26  891.31   55.81   914.9   55.69  934.62   68.18  946.89   70.52
 1027.94    70.6 1118.59   68.21 1355.19   69.56 1477.59   69.45 1524.42    68.3
 1561.25   69.02 1743.47   68.35 1960.43   69.72 1997.59   67.27 2055.11   70.06
 2276.37   71.08 2804.34   70.33 2991.49   68.12 3064.22   70.79 3140.05   70.87
#Mann= 3 , 0 , 0
       0     .15       0  855.26    .015       0  946.89     .15       0
#XS Ineff= 2 , 0
       0     686            1119       0
Permanent Ineff=
       T       T
Bank Sta=855.26,946.89
XS Rating Curve= 0
Exp/Cntr=.3,.1

Type RM Length L Ch R = 1 ,5890    ,40.26,39.93,40.05
XS GIS Cut Line= 4
     3066499.061    13818623.815     3065615.861     13818807.18
     3065556.209    13818831.572     3063512.647    13819602.046
#Sta/Elev= 30
       0   69.19  639.92   70.43   701.2   69.72  731.84   66.69   795.2   69.74
  885.04   70.88  896.69   69.71  922.33   55.99  942.43   55.91     962   68.21
  969.11   69.53 1029.22   70.72 1082.61   70.45 1117.54   68.67  1164.1   70.43
 1233.95   70.83 1718.54   70.96 1734.54   70.32 1932.45   71.05 1967.37   70.27
  2007.1   67.91 2055.19   70.43 2165.28   70.31 2398.11   68.09 2526.17   69.95
 2840.69   70.54 2980.18    70.1 3038.39   68.21 3097.18   70.74 3150.46   70.73
#Mann= 3 , 0 , 0
       0     .15       0  896.69    .015       0  969.11     .15       0
#XS Ineff= 2 , 0
       0     722            1152       0
Permanent Ineff=
       T       T
Bank Sta=896.69,969.11
XS Rating Curve= 0
Exp/Cntr=.5,.3

Type RM Length L Ch R = 1 ,5850    ,72.43,71.83,71.98
XS GIS Cut Line= 4
     3066492.031    13818584.427     3065604.839     13818768.62
     3065545.187    13818793.012     3063514.451    13819558.599
#Sta/Elev= 30
       0   68.19  124.83   69.52  617.42   69.43  683.02   69.03  739.98   66.93
  785.94   68.89  873.31   70.02  893.18   69.76   904.9   68.17  907.56   68.81
  932.33   55.99  952.43   55.91     972   68.21  991.65   70.46 1085.64   69.69
  1117.7   68.35  1165.8   70.04 1245.95   70.67 1678.77    70.2  1899.7   71.05
 1967.32    70.3 2015.42   67.93 2047.48    69.9 2097.61   70.85 2377.01   70.09
 2493.42    68.6 2945.19    70.5 3025.34   68.23 3073.43   70.18 3140.81   70.58
#Mann= 3 , 0 , 0
       0     .15       0  907.56    .015       0     972     .15       0
#XS Ineff= 2 , 0
       0     728            1160       0
Permanent Ineff=
       T       T
Bank Sta=907.56,972
XS Rating Curve= 0
Exp/Cntr=.5,.3

Type RM Length L Ch R = 2 ,5804    ,,,
BEGIN DESCRIPTION:
Rowan Box Culverts
END DESCRIPTION:
Bridge Culvert--1,0,-1,-1, 0
Deck Dist Width WeirC Skew NumUp NumDn MinLoCord MaxHiCord MaxSubmerge Is_Ogee
5,40,2.6,0, 5, 5, , , .95, 0, 0,0,,
  907.57  930.32  940.32  951.82  971.98
   68.81   66.72   66.81   66.79   68.18
       0       0       0       0       0
  913.57  936.32  946.32  957.82     978
   68.81   66.72   66.81   66.79    68.2
       0       0       0       0       0
Multiple Barrel Culv=2,10,10,40,.015,.5,1,8,2,56.12,56.12, 2,Culvert #1  , 0 ,5
  937.07  943.07  947.57  953.57
Culvert Bottom n=.015
BC Design=,, 0 ,, 0 ,,,,,,

Type RM Length L Ch R = 1 ,5778    ,198.94,195.88,203.84
BEGIN DESCRIPTION:
Survey
END DESCRIPTION:
XS GIS Cut Line= 4
     3066479.383    13818513.569     3065584.901    13818699.275
      3065525.25    13818723.668     3063517.585    13819483.123
#Sta/Elev= 30
       0   67.33   59.89   66.16   97.95   66.96  541.96   65.65  656.14   67.57
  744.94   67.14  803.66   69.31  895.58   70.24   910.9   68.17  913.56   68.81
  938.33   55.99  958.43   55.91     978   68.21  991.63   70.03 1007.67   70.69
 1142.13   68.47 1200.12   70.01 1601.05   68.47  1921.8   70.47 1969.91   70.08
 2014.81   68.23 2038.08   70.14 2114.25   71.09 2538.42   70.35  2739.7   68.29
 2854.24    70.1 2932.15   70.03 3015.49   67.89 3060.45   69.89 3124.51   70.46
#Mann= 3 , 0 , 0
       0     .15       0  913.56    .015       0     978     .15       0
#XS Ineff= 2 , 0
       0     738            1174       0
Permanent Ineff=
       T       T
Bank Sta=913.56,978
XS Rating Curve= 0
Exp/Cntr=.5,.3

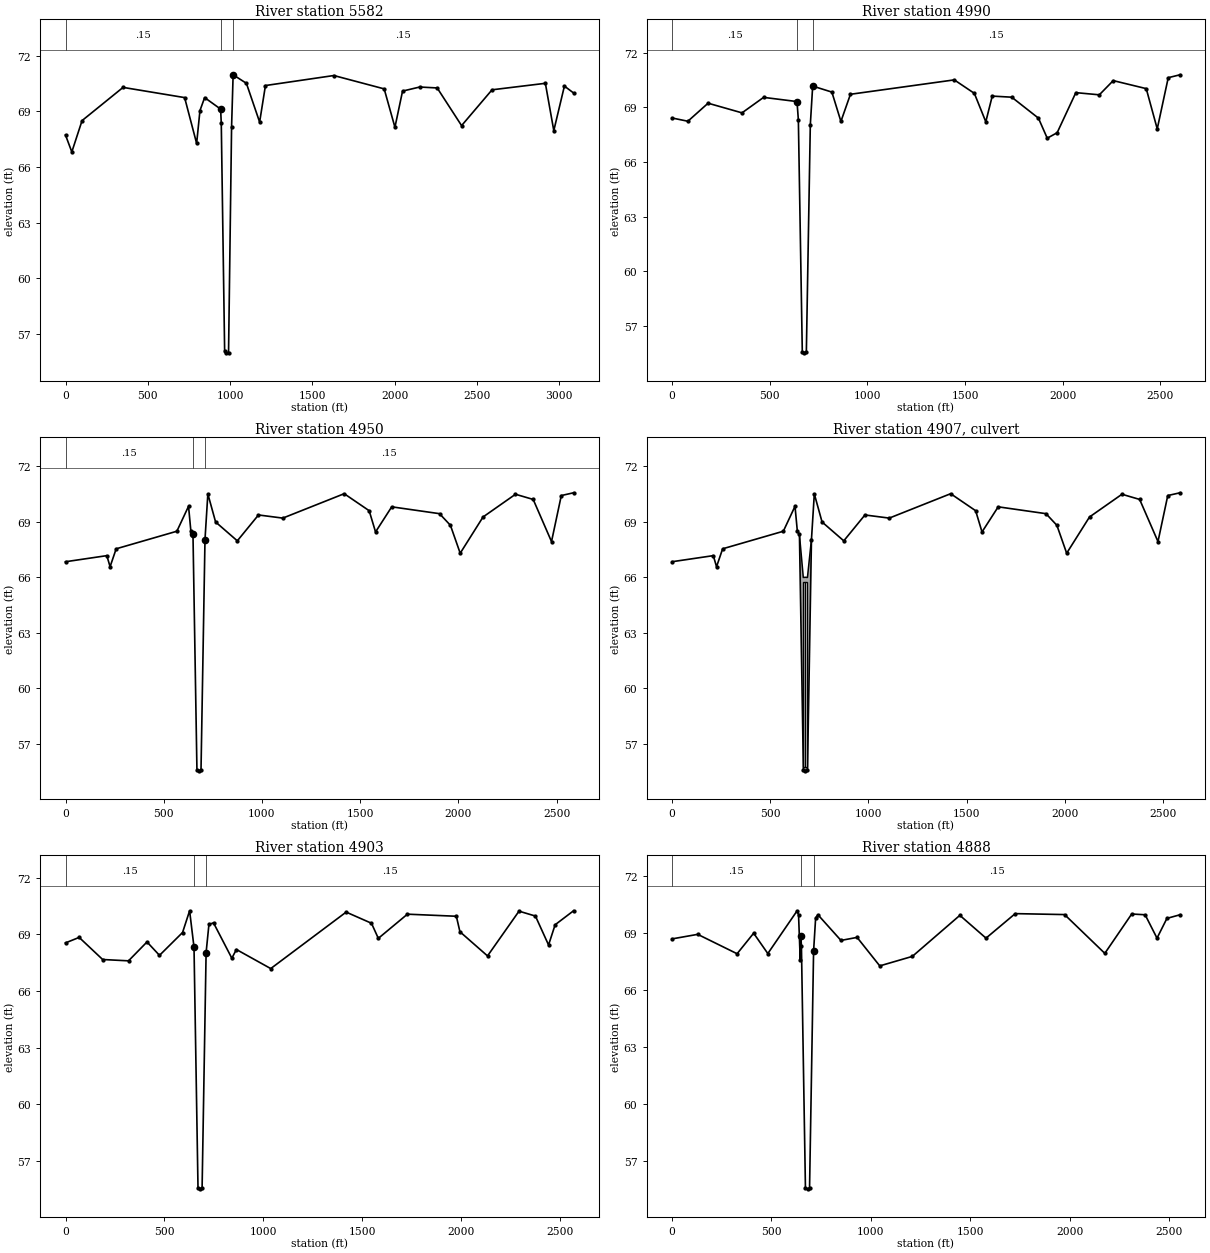
Type RM Length L Ch R = 1 ,5582    ,597.28,591.67,591.29
BEGIN DESCRIPTION:
Survey
END DESCRIPTION:
XS GIS Cut Line= 4
     3066434.456    13818261.874     3065526.565    13818516.267
     3065461.221     13818529.52     3063525.702    13819287.663
#Sta/Elev= 30
       0   67.72   38.38   66.81  100.69    68.5  349.93   70.29  724.07   69.74
  797.08   67.27  817.27   69.04  845.75   69.74  942.86   69.12  946.85   68.36
  967.34   56.07   978.5   55.98  991.09   55.99 1009.53   68.17  1018.9   70.97
 1099.59   70.51    1180   68.42 1215.35   70.39 1631.07   70.93 1937.15   70.21
 2002.48   68.14 2048.78   70.09 2152.96   70.31 2259.34   70.26 2407.63   68.23
 2592.84   70.16 2916.95   70.51 2968.17   67.96 3032.61   70.36 3088.24   69.99
#Mann= 3 , 0 , 0
       0     .15       0  942.86    .015       0  1018.9     .15       0
#XS Ineff= 2 , 0
       0     768            1210       0
Permanent Ineff=
       T       T
Bank Sta=942.86,1018.9
XS Rating Curve= 0
Exp/Cntr=.3,.1

Type RM Length L Ch R = 1 ,4990    ,40.16,40.26,40.12
XS GIS Cut Line= 5
     3065958.116    13817750.408     3065342.458    13817952.575
     3065280.064     13817967.25     3064453.281     13818290.91
     3063549.292    13818719.586
#Sta/Elev= 30
       0   68.42   81.38   68.24  184.84   69.23  358.51    68.7  469.03   69.55
  639.99   69.32  646.92   68.32  667.08    55.6  677.49   55.53  687.81   55.57
   708.1   68.04  720.22   70.17  818.46   69.84  864.76   68.23  913.52   69.72
  1445.1   70.51 1547.78   69.77 1606.37   68.21 1639.29   69.62 1739.18   69.56
 1875.77   68.41 1920.82   67.31  1971.6   67.61 2067.21   69.81 2187.41   69.69
 2258.65   70.47 2427.56   70.03 2483.87   67.82 2540.17   70.63 2600.45   70.79
#Mann= 3 , 0 , 0
       0     .15       0  639.99    .015       0  720.22     .15       0
#XS Ineff= 2 , 0
       0     455             890       0
Permanent Ineff=
       T       T
Bank Sta=639.99,720.22
XS Rating Curve= 0
Exp/Cntr=.5,.3

Type RM Length L Ch R = 1 ,4950    ,46.64,46.71,46.62
XS GIS Cut Line= 5
     3065947.233    13817711.708     3065331.575    13817913.875
     3065269.181     13817928.55     3064442.398     13818252.21
     3063551.149    13818674.844
#Sta/Elev= 30
       0   66.84  210.39   67.17  226.91   66.57  257.93   67.54  566.94   68.49
  626.37   69.84  638.26   68.49  648.92   68.32  669.08    55.6  679.49   55.53
  689.81   55.57   710.1   68.04  724.64   70.51  764.08   68.99  874.66   67.97
  982.38   69.37 1106.19    69.2 1418.75   70.52 1545.91    69.6 1578.39   68.45
 1660.73   69.81 1904.06   69.44 1959.55   68.81 2009.36    67.3 2125.56   69.26
 2290.79   70.49 2380.88   70.21 2474.19   67.93 2523.99   70.42 2586.35   70.57
#Mann= 3 , 0 , 0
       0     .15       0  648.92    .015       0   710.1     .15       0
#XS Ineff= 2 , 0
       0     454             883       0
Permanent Ineff=
       T       T
Bank Sta=648.92,710.1
XS Rating Curve= 0
Exp/Cntr=.5,.3

Type RM Length L Ch R = 2 ,4907    ,,,
BEGIN DESCRIPTION:
Sharpview Box Culverts
END DESCRIPTION:
Bridge Culvert--1,0,-1,-1, 0
Deck Dist Width WeirC Skew NumUp NumDn MinLoCord MaxHiCord MaxSubmerge Is_Ogee
5,40,2.6,0, 5, 5, , , .95, 0, 0,0,,
  648.92  668.61  679.11  689.61  710.12
   68.31   65.99      66   65.99   68.06
       0       0       0       0       0
  649.92  669.61  680.11  690.61  711.09
    68.3   65.99      66   65.99   68.02
       0       0       0       0       0
Multiple Barrel Culv=2,10,10,40,.015,.5,1,8,2,55.73,55.73, 2,Culvert #1  , 0 ,5
  673.86  674.86  684.36  685.36
Culvert Bottom n=.015
BC Design=,, 0 ,, 0 ,,,,,,

Type RM Length L Ch R = 1 ,4903    ,15.21,15.29,15.17
XS GIS Cut Line= 5
     3065934.093    13817666.932     3065318.435      13817869.1
     3065256.041    13817883.775     3064429.258    13818207.435
      3063553.31    13818622.813
#Sta/Elev= 30
       0   68.55   69.06   68.84  187.91   67.67  318.65    67.6  412.17    68.6
  475.32   67.89  592.01    69.1  627.67   70.25  649.92   68.32  670.08    55.6
  680.49   55.53  690.81   55.57   711.1   68.04  725.42   69.53  748.58   69.61
  841.19   67.74  864.34    68.2 1037.99   67.19  1419.3   70.18 1547.36   69.59
 1582.09   68.79  1729.2   70.07 1976.71   69.96 1994.81   69.14 2134.37   67.86
 2293.63   70.23 2376.64   69.97 2443.04   68.44 2476.25   69.51 2569.42   70.25
#Mann= 3 , 0 , 0
       0     .15       0  649.92    .015       0   711.1     .15       0
#XS Ineff= 2 , 0
       0     456             854       0
Permanent Ineff=
       T       T
Bank Sta=649.92,711.1
XS Rating Curve= 0
Exp/Cntr=.5,.3

Type RM Length L Ch R = 1 ,4888    ,364.59,361.63,372.22
BEGIN DESCRIPTION:
Survey
END DESCRIPTION:
XS GIS Cut Line= 5
     3065930.411    13817652.128     3065314.753    13817854.296
      3065252.36    13817868.971     3064425.577    13818192.631
     3063562.997     13818601.67
#Sta/Elev= 30
       0   68.68   129.4   68.92  327.46    67.9  410.66   68.98  481.97   67.91
  629.32   70.16  636.48   69.94  645.11   67.55     648   68.81  650.92   68.32
  671.08    55.6  681.49   55.53  691.81   55.57   712.1   68.04  722.43   69.79
  734.01   69.95  849.77    68.6  930.81   68.76 1044.85   67.26 1208.65   67.76
 1447.56   69.92  1579.1   68.72 1726.06   70.01 1974.14   69.96  2176.5   67.92
 2311.63   69.99  2379.2   69.95 2438.97   68.72 2488.77   69.76 2554.62   69.95
#Mann= 3 , 0 , 0
       0     .15       0     648    .015       0   712.1     .15       0
#XS Ineff= 2 , 0
       0     458             846       0
Permanent Ineff=
       T       T
Bank Sta=648,712.1
XS Rating Curve= 0
Exp/Cntr=.3,.1

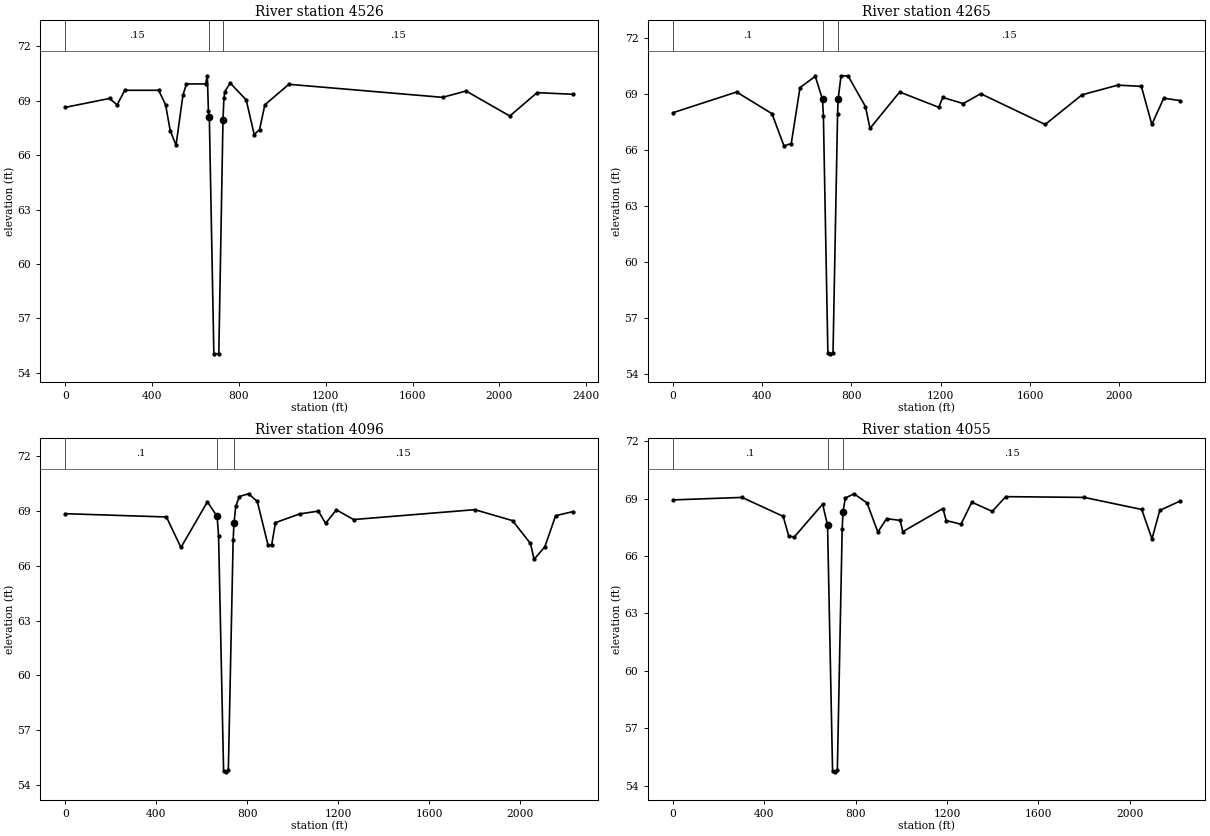
Type RM Length L Ch R = 1 ,4526    ,264.82,261.01,259.82
BEGIN DESCRIPTION:
Survey
END DESCRIPTION:
XS GIS Cut Line= 4
     3065824.328    13817277.513      3065207.91    13817509.808
     3065141.712    13817521.316     3063582.212    13817926.806
#Sta/Elev= 30
       0   68.64  203.21   69.13  238.14   68.77  273.06   69.58  429.41   69.58
  461.47   68.78  482.63   67.36  509.56   66.55  541.62   69.33  557.65   69.93
  645.62   69.93  653.83   70.38  658.74   68.43  663.06   68.08  683.85   55.04
  706.67   55.05  725.93   67.95  730.28   69.16  734.45   69.51  759.05   69.98
  832.86   69.05  869.72   67.14  894.36   67.41  918.96   68.78 1029.66   69.91
  1737.7   69.19 1846.19   69.54 2047.67   68.16 2173.61   69.45 2337.28   69.36
#Mann= 3 , 0 , 0
       0     .15       0  663.06    .015       0  725.93     .15       0
#XS Ineff= 2 , 0
       0     477             744       0
Permanent Ineff=
       T       T
Bank Sta=663.06,725.93
XS Rating Curve= 0
Exp/Cntr=.3,.1

Type RM Length L Ch R = 1 ,4265    ,169.26,169.75,169.31
BEGIN DESCRIPTION:
Survey
END DESCRIPTION:
XS GIS Cut Line= 4
     3065744.752    13816996.834     3065128.948    13817261.316
     3065062.315    13817271.782      3063591.33    13817707.244
#Sta/Elev= 30
       0   67.99  285.42    69.1   443.8   67.94  497.64   66.21  530.29   66.34
  569.42   69.34  637.94   69.94   670.2    68.7  674.19   67.81  694.28    55.1
  704.17   55.07  717.33   55.12  737.65   67.92  740.18   68.72   753.1   69.96
  784.39   69.97   862.6   68.32  882.92   67.15 1015.69    69.1 1191.12   68.28
 1208.82   68.81 1300.62   68.48 1378.84   69.01 1667.49   67.36  1832.5   68.95
 1993.38   69.47 2098.44    69.4 2145.37   67.36 2198.58   68.77 2271.74   68.64
#Mann= 3 , 0 , 0
       0      .1       0   670.2    .015       0  740.18     .15       0
#XS Ineff= 2 , 0
       0     483             760       0
Permanent Ineff=
       T       T
Bank Sta=670.2,740.18
XS Rating Curve= 0
Exp/Cntr=.3,.1

Type RM Length L Ch R = 1 ,4096    ,39.77,40.4,40.01
XS GIS Cut Line= 4
     3065694.228    13816829.483     3065082.354    13817098.759
     3065001.262     13817111.61     3063596.546    13817581.644
#Sta/Elev= 30
       0   68.85  444.37   68.67  508.12      67  624.64    69.5  667.44    68.7
  673.89   67.61  695.88   54.75   708.2   54.72  716.76    54.8  737.88    67.4
  741.61   68.32  749.36   69.25  765.12   69.79  805.64   69.94  844.21   69.52
  891.66   67.12  907.48   67.14  924.16   68.36 1030.83   68.84 1113.11   68.99
 1144.74   68.32 1192.19   69.06 1267.86   68.53 1801.19   69.07 1967.25   68.47
 2046.34   67.22 2062.15   66.35 2109.61   67.04 2157.06   68.74 2231.88   68.96
#Mann= 3 , 0 , 0
       0      .1       0  667.44    .015       0  741.61     .15       0
#XS Ineff= 2 , 0
       0     486             764       0
Permanent Ineff=
       T       T
Bank Sta=667.44,741.61
XS Rating Curve= 0
Exp/Cntr=.5,.3

Type RM Length L Ch R = 1 ,4055    ,50.85,51.96,51.27
XS GIS Cut Line= 4
     3065684.369    13816790.603     3065072.495    13817059.879
     3064991.403     13817072.73     3063598.322    13817538.871
#Sta/Elev= 30
       0   68.93  302.62   69.06  482.77   68.07  507.37   67.02  531.93      67
  655.32   68.71  676.89   67.61  698.88   54.75   711.2   54.72  719.76    54.8
  740.88    67.4  744.61   68.32  754.73   69.03  793.02   69.25  849.63   68.77
  897.08   67.25  935.24   67.95   994.5   67.86 1006.35   67.27  1181.8   68.48
 1195.98   67.85 1260.88   67.66 1308.34   68.81 1397.46   68.33 1456.71    69.1
 1800.41   69.06 2051.76   68.43 2096.71   66.89 2130.84   68.38 2219.61   68.87
#Mann= 3 , 0 , 0
       0      .1       0  676.89    .015       0  744.61     .15       0
#XS Ineff= 2 , 0
       0     488             767       0
Permanent Ineff=
       T       T
Bank Sta=676.89,744.61
XS Rating Curve= 0
Exp/Cntr=.5,.3