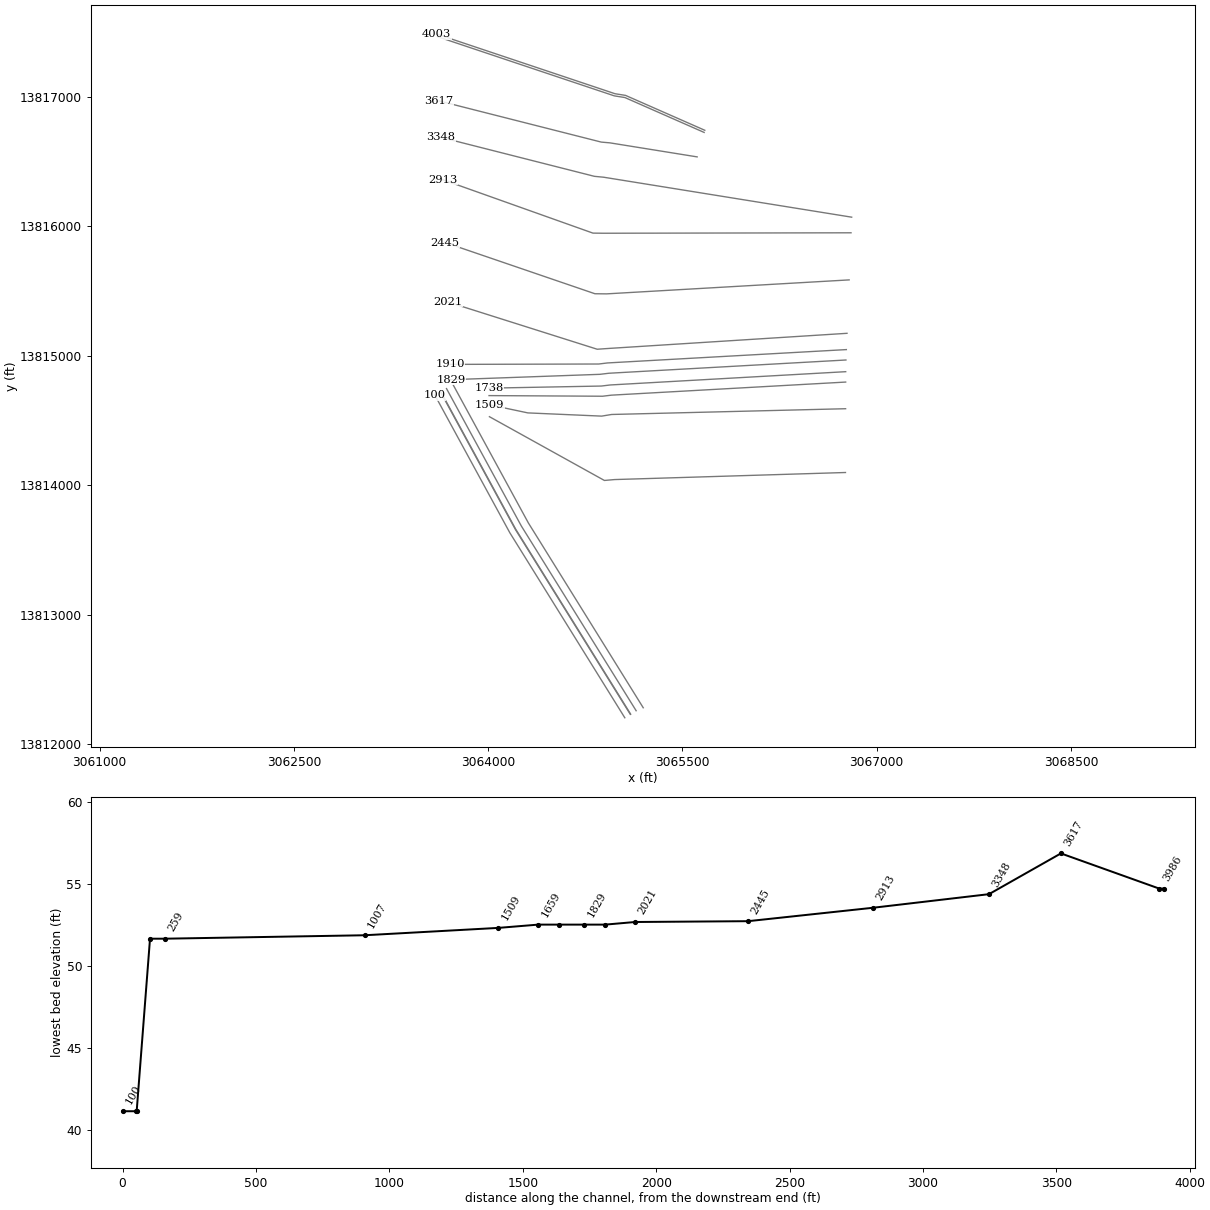
HEC-RAS study D142-00-00.prj: D142-00-00

--- D142-00-00.g03 (geometry) --- (continued)

Type RM Length L Ch R = 2 ,4008    ,,,
BEGIN DESCRIPTION:
Carvel Box Culverts
END DESCRIPTION:
Bridge Culvert--1,0,-1,-1, 0
Deck Dist Width WeirC Skew NumUp NumDn MinLoCord MaxHiCord MaxSubmerge Is_Ogee
5,40,2.6,0, 5, 5, , , .95, 0, 0,0,,
  676.89   698.4   708.9   719.4  740.94
    67.6   65.64   65.63   65.64   67.39
       0       0       0       0       0
  680.89   703.4   713.9   724.4  744.88
    67.6   65.64   65.63   65.64   67.39
       0       0       0       0       0
Multiple Barrel Culv=2,10,10,40,.015,.5,1,8,2,54.9,54.8, 2,Culvert #1  , 0 ,5
  703.65  708.65  714.15  719.15
Culvert Bottom n=.015
BC Design=,, 0 ,, 0 ,,,,,,

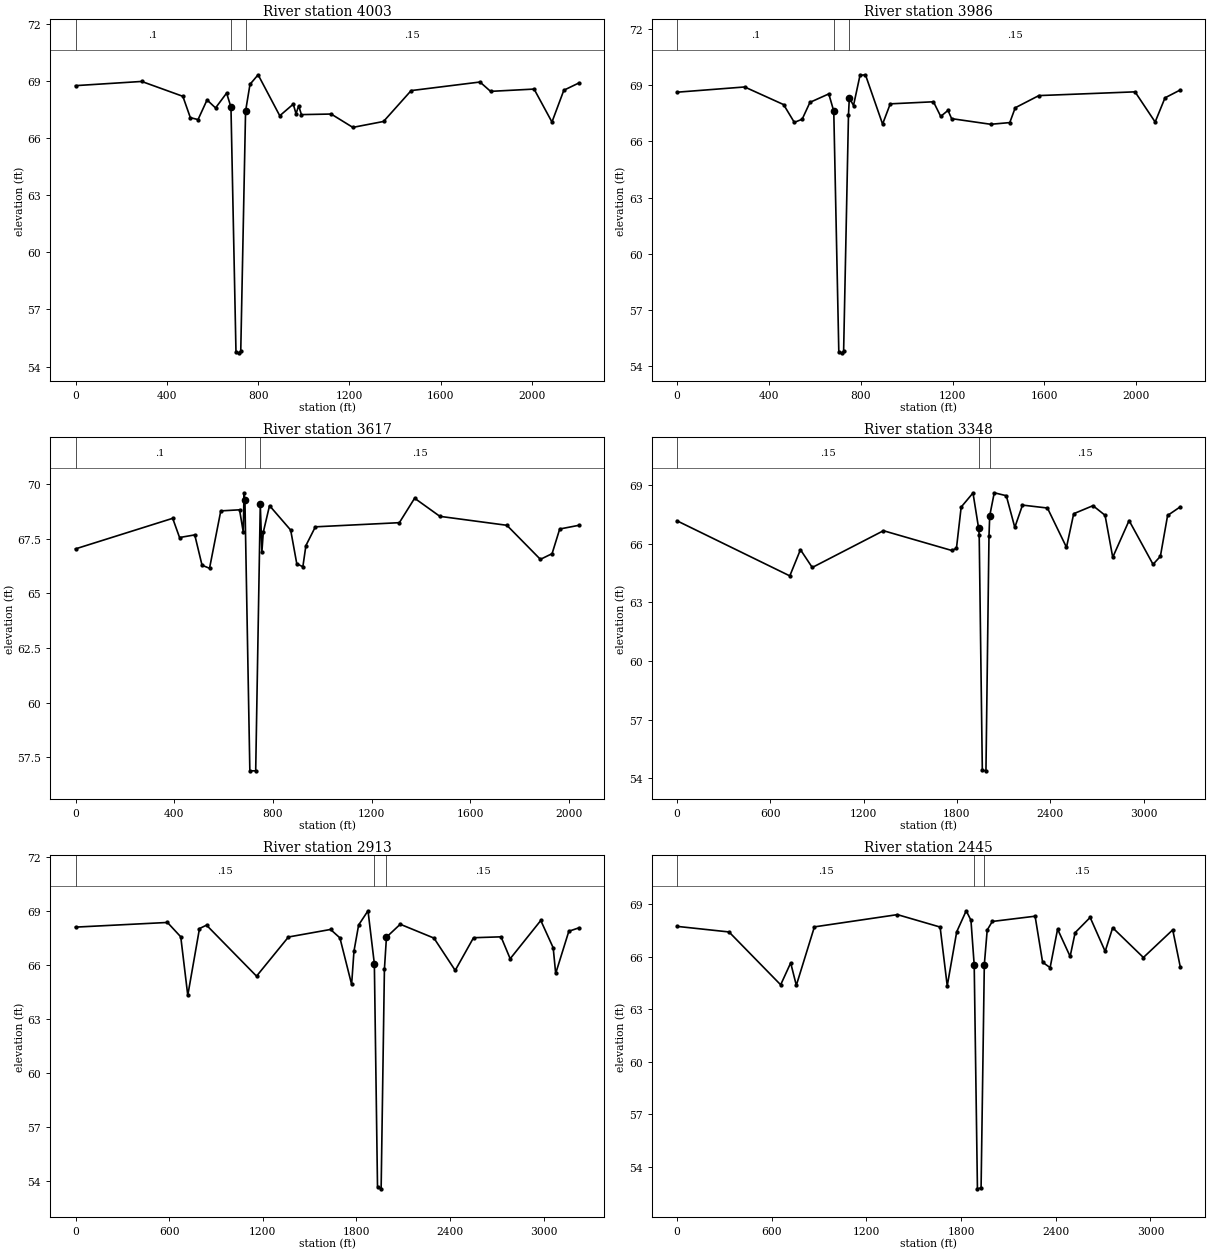
Type RM Length L Ch R = 1 ,4003    ,17.34,17.38,17.36
XS GIS Cut Line= 4
     3065672.814    13816740.424     3065060.941      13817009.7
     3064979.849    13817022.551     3063600.598    13817484.064
#Sta/Elev= 30
       0   68.74  289.87   68.96  470.14   68.18  502.92   67.06  536.68   66.96
  576.15   67.99  613.39   67.57  661.86   68.35  680.89   67.61  702.88   54.75
   715.2   54.72  723.76    54.8  744.88    67.4  764.28   68.81  799.83   69.31
  894.65   67.16   953.9   67.77  965.76   67.27  977.61   67.68  989.46   67.22
 1119.83   67.25 1214.64   66.55 1349.22   66.86 1470.14   68.48 1771.67   68.93
 1818.13   68.44 2008.71   68.56 2087.03   66.83 2139.08    68.5 2205.03   68.88
#Mann= 3 , 0 , 0
       0      .1       0  680.89    .015       0  744.88     .15       0
#XS Ineff= 2 , 0
       0     493             771       0
Permanent Ineff=
       T       T
Bank Sta=680.89,744.88
XS Rating Curve= 0
Exp/Cntr=.5,.3

Type RM Length L Ch R = 1 ,3986    ,346.6,368.68,375.01
BEGIN DESCRIPTION:
Survey
END DESCRIPTION:
XS GIS Cut Line= 4
     3065667.677    13816723.844     3065055.804     13816993.12
     3064974.711    13817005.971     3063608.938    13817462.974
#Sta/Elev= 30
       0   68.62     295    68.9  464.53   67.96  511.22   67.01  545.36   67.18
  579.25   68.08  661.19   68.53  682.89   67.61  704.88   54.75   717.2   54.72
  725.76    54.8  746.88    67.4  750.61   68.32  768.76   67.91  797.02   69.52
  820.72   69.55   895.3   66.92  928.75      68 1116.74   68.11 1148.38   67.33
 1180.01   67.65 1195.83   67.21  1365.9   66.91 1448.91      67 1472.57   67.79
 1575.45   68.44 1994.05   68.64 2081.61   67.03 2124.41   68.32 2190.81   68.74
#Mann= 3 , 0 , 0
       0      .1       0  682.89    .015       0  750.61     .15       0
#XS Ineff= 2 , 0
       0     493             771       0
Permanent Ineff=
       T       T
Bank Sta=682.89,750.61
XS Rating Curve= 0
Exp/Cntr=.3,.1

Type RM Length L Ch R = 1 ,3617    ,270.24,269.59,270.69
BEGIN DESCRIPTION:
Survey
END DESCRIPTION:
XS GIS Cut Line= 4
     3065613.807    13816534.963     3064939.519    13816643.404
     3064873.831    13816649.114     3063622.077    13816966.823
#Sta/Elev= 30
       0   67.04  393.85   68.44  421.66   67.56  483.24   67.68  512.81   66.29
   543.2   66.15  588.78   68.78  664.86   68.83  679.93   67.81  682.95   69.61
  686.61   69.27   706.6   56.87  730.28   56.87  748.89   69.08  755.42    66.9
     761    67.8  786.37   69.02  872.08    67.9  896.77   66.36  921.46   66.22
   933.8   67.19  972.08   68.05 1312.54   68.24 1374.44   69.36 1476.88   68.53
 1748.43   68.12  1884.2   66.56 1931.57   66.82 1962.52   67.95 2040.33   68.12
#Mann= 3 , 0 , 0
       0      .1       0  686.61    .015       0  748.89     .15       0
#XS Ineff= 2 , 0
       0     498             757       0
Permanent Ineff=
       T       T
Bank Sta=686.61,748.89
XS Rating Curve= 0
Exp/Cntr=.3,.1

Type RM Length L Ch R = 1 ,3348    ,414.74,434.38,437.72
BEGIN DESCRIPTION:
Survey
END DESCRIPTION:
XS GIS Cut Line= 4
      3066806.72    13816069.529     3064891.874    13816377.998
     3064820.836    13816384.807     3063633.734    13816686.108
#Sta/Elev= 30
       0   67.17  725.97   64.35  794.33   65.69   870.3   64.78  1327.9   66.66
 1766.71   65.65 1797.09   65.76 1827.48   67.87 1903.45   68.59 1939.53   66.79
 1943.29   66.45 1963.44   54.41 1986.72   54.38 2006.29   66.39  2010.9   67.42
 2040.13    68.6 2117.51   68.45  2172.2   66.83 2221.57   67.97 2382.03   67.82
  2504.4   65.81 2550.83   67.53 2674.63   67.94 2752.31   67.45 2801.69    65.3
 2906.77   67.18 3060.88   64.94 3107.95   65.35 3154.38   67.44 3235.64   67.88
#Mann= 3 , 0 , 0
       0     .15       0 1939.53    .015       0  2010.9     .15       0
#XS Ineff= 2 , 0
       0    1771            2020       0
Permanent Ineff=
       T       T
Bank Sta=1939.53,2010.9
XS Rating Curve= 0
Exp/Cntr=.3,.1

Type RM Length L Ch R = 1 ,2913    ,462.54,468.43,470.52
BEGIN DESCRIPTION:
Survey
END DESCRIPTION:
XS GIS Cut Line= 4
     3066801.883    13815948.946     3064890.786    13815945.473
     3064809.303    13815946.479     3063647.282    13816359.832
#Sta/Elev= 30
       0   68.12  589.01   68.38  674.38   67.58  719.38   64.32  794.38   68.04
  839.38   68.23 1160.05   65.39 1364.39   67.57 1634.39   67.99 1694.39   67.52
 1769.39   64.93 1784.39   66.78 1814.39   68.24 1874.39   69.03 1915.04   66.08
 1935.25   53.68  1958.5   53.55 1979.53   65.77 1992.59   67.56 2080.92   68.28
    2297   67.51 2433.22   65.71 2550.66   67.53 2726.86   67.58 2785.52   66.36
 2981.59   68.49 3061.19   66.97 3077.12   65.54 3161.31   67.89 3225.94   68.08
#Mann= 3 , 0 , 0
       0     .15       0 1915.04    .015       0 1992.59     .15       0
#XS Ineff= 2 , 0
       0    1750            1999       0
Permanent Ineff=
       T       T
Bank Sta=1915.04,1992.59
XS Rating Curve= 0
Exp/Cntr=.3,.1

Type RM Length L Ch R = 1 ,2445    ,421.14,423.44,429.77
BEGIN DESCRIPTION:
Survey
END DESCRIPTION:
XS GIS Cut Line= 4
     3066787.296    13815585.317     3064914.244    13815477.412
      3064824.59    13815478.419      3063667.46    13815873.928
#Sta/Elev= 30
       0   67.73  330.34   67.41  657.52   64.39  720.99   65.64  756.76   64.36
  871.24    67.7 1397.11    68.4 1667.56   67.69 1712.63   64.33 1772.73   67.42
 1832.83   68.62 1862.88   68.08 1883.51   65.51 1903.94   52.73 1927.07   52.79
 1947.58   65.54 1965.82   67.52 1998.24   68.01 2269.22   68.31 2316.77   65.68
 2364.33   65.37 2411.73   67.57 2491.14   66.01 2522.85   67.37 2617.96   68.24
 2713.07    66.3 2760.63   67.65 2955.18   65.95 3141.08   67.53 3188.67   65.42
#Mann= 3 , 0 , 0
       0     .15       0 1883.51    .015       0 1947.58     .15       0
#XS Ineff= 2 , 0
       0    1723            1987       0
Permanent Ineff=
       T       T
Bank Sta=1883.51,1947.58
XS Rating Curve= 0
Exp/Cntr=.3,.1

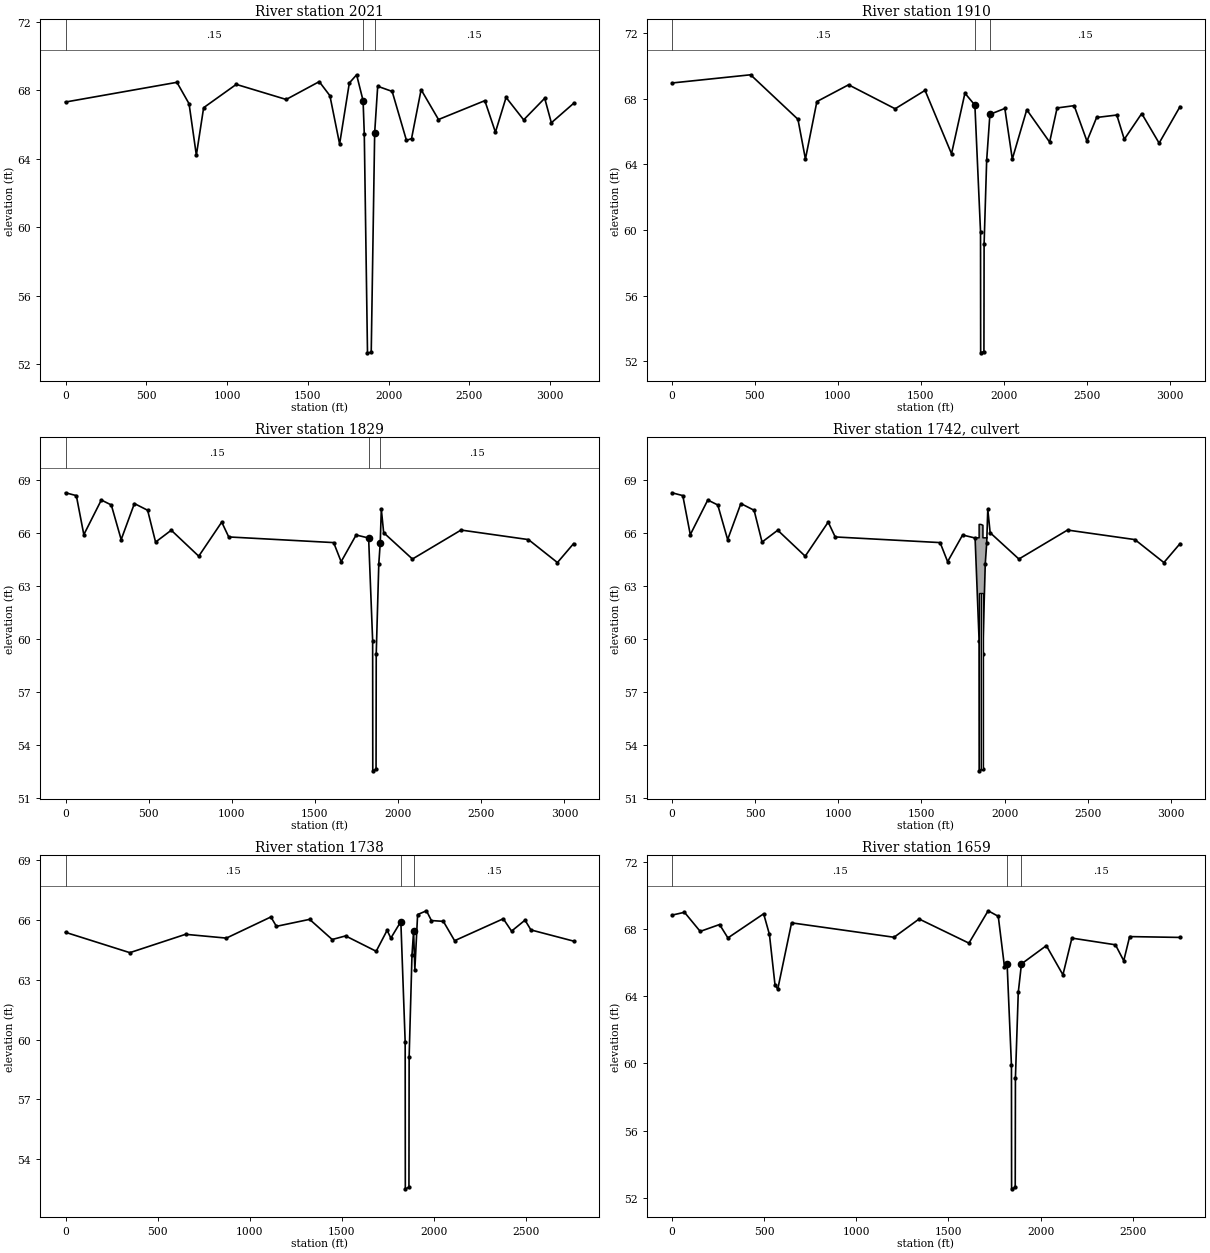
Type RM Length L Ch R = 1 ,2021    ,112.04,111.49,125.71
BEGIN DESCRIPTION:
Survey
END DESCRIPTION:
XS GIS Cut Line= 4
     3066770.753    13815172.913     3064932.512    13815056.218
     3064842.339    13815050.002     3063686.492     13815415.61
#Sta/Elev= 30
       0   67.31  689.64   68.46  764.79   67.21  809.88   64.21  854.97   66.98
 1056.92   68.34    1366   67.46 1570.49    68.5 1636.54   67.68 1696.66   64.86
 1756.78   68.42 1801.87    68.9 1841.94   67.39 1849.35   65.44 1869.24   52.68
 1892.29    52.7 1913.66   65.52 1932.33   68.23 2021.84   67.93 2110.46   65.07
 2141.93   65.18 2201.12   68.03 2308.69   66.29 2595.53   67.39  2661.1   65.55
    2727   67.58 2835.88   66.27 2966.04   67.53 3007.21    66.1 3144.62   67.23
#Mann= 3 , 0 , 0
       0     .15       0 1841.94    .015       0 1913.66     .15       0
#XS Ineff= 2 , 0
       0    1676            1984       0
Permanent Ineff=
       T       T
Bank Sta=1841.94,1913.66
XS Rating Curve= 0
Exp/Cntr=.3,.1

Type RM Length L Ch R = 1 ,1910    ,80.03,80.41,81.3
XS GIS Cut Line= 4
     3066765.712     13815047.24     3064922.512     13814944.22
      3064853.82    13814935.897     3063706.532    13814933.032
#Sta/Elev= 30
       0   68.95  473.95   69.45   759.4   66.74  804.47   64.32  873.58   67.82
 1064.54   68.84 1345.31   67.38 1525.59    68.5 1685.14   64.64 1765.96   68.33
 1826.06    67.6 1860.01   59.89 1860.84   52.52  1880.5    52.6 1881.57   59.14
 1897.03   64.24 1916.59   67.04 2006.59    67.4 2051.59   64.32 2138.75   67.32
 2276.59   65.35 2321.59   67.43 2424.47   67.57 2501.59   65.41 2559.81   66.85
 2681.59      67 2726.59   65.52 2831.59   67.09 2936.59   65.29 3062.56   67.51
#Mann= 3 , 0 , 0
       0     .15       0 1826.06    .015       0 1916.59     .15       0
#XS Ineff= 2 , 0
       0    1660            1942       0
Permanent Ineff=
       T       T
Bank Sta=1826.06,1916.59
XS Rating Curve= 0
Exp/Cntr=.5,.3

Type RM Length L Ch R = 1 ,1829    ,90.93,91.43,89.85
XS GIS Cut Line= 4
     3066762.491    13814966.929       3064932.1     13814864.63
     3064863.408    13814856.307      3063711.44    13814814.823
#Sta/Elev= 30
       0   68.26   65.09    68.1  110.16   65.89  215.33   67.85  275.42   67.57
  334.76   65.61  414.33   67.65  493.89   67.27  541.63   65.47  635.98   66.14
  801.24   64.67  939.45    66.6  981.52   65.76  1612.5   65.44 1657.57   64.36
 1747.71   65.87 1822.83    65.7 1847.01   59.89 1847.84   52.52  1867.5    52.6
 1868.57   59.14 1884.03   64.24 1892.75   65.43 1899.12   67.33 1913.36      66
 2086.28   64.51 2378.66   66.15 2783.92   65.61 2958.22   64.31 3055.16   65.38
#Mann= 3 , 0 , 0
       0     .15       0 1822.83    .015       0 1892.75     .15       0
#XS Ineff= 2 , 0
       0    1646            1932       0
Permanent Ineff=
       T       T
Bank Sta=1822.83,1892.75
XS Rating Curve= 0
Exp/Cntr=.5,.3

Type RM Length L Ch R = 2 ,1742    ,,,
BEGIN DESCRIPTION:
Beechnut Box Culverts
END DESCRIPTION:
Bridge Culvert--1,0,-1,-1, 0
Deck Dist Width WeirC Skew NumUp NumDn MinLoCord MaxHiCord MaxSubmerge Is_Ogee
5,80,2.6,0, 7, 7, , , .95, 0, 0,0,,
    1820 1847.03 1847.03 1857.78 1870.03 1870.03    1895
   65.71   65.71   66.47   66.47   66.42   65.71   65.71
       0       0       0       0       0       0       0
    1820 1843.69 1843.69 1854.44 1866.69 1866.69 1889.74
   65.91   65.91   66.47   66.47   66.42   65.91   65.43
       0       0       0       0       0       0       0
Multiple Barrel Culv=2,10,10,80,.015,.7,1,8,3,52.6,52.6, 2,Culvert #1  , 0 ,5
 1852.53 1849.19 1863.03 1859.69
Culvert Bottom n=.015
BC Design=,, 0 ,, 0 ,,,,,,

Type RM Length L Ch R = 1 ,1738    ,79.13,79.46,77.34
BEGIN DESCRIPTION:
Survey
END DESCRIPTION:
XS GIS Cut Line= 4
     3066760.664    13814876.688        3064943.    13814774.152
     3064874.308     13814765.83     3064006.087    13814749.614
#Sta/Elev= 30
       0   65.38   349.2   64.36  651.72   65.28  873.35   65.09 1114.93   66.15
 1144.98   65.68 1325.27   66.03 1447.82   65.02 1520.58    65.2 1686.65   64.43
 1745.94   65.48 1766.26   65.09 1820.55   65.92 1844.01   59.89 1844.84   52.52
  1864.5    52.6 1865.57   59.14 1881.03   64.24 1889.75   65.43 1896.56   63.51
 1911.56   66.27 1959.54   66.46 1986.57   65.97 2051.27   65.93 2112.42   64.96
 2376.64   66.06 2421.65   65.44 2494.63   65.99 2526.67    65.5 2758.12   64.94
#Mann= 3 , 0 , 0
       0     .15       0 1820.55    .015       0 1889.75     .15       0
#XS Ineff= 2 , 0
       0    1633            1930       0
Permanent Ineff=
       T       T
Bank Sta=1820.55,1889.75
XS Rating Curve= 0
Exp/Cntr=.5,.3

Type RM Length L Ch R = 1 ,1659    ,151.92,149.73,151.92
XS GIS Cut Line= 4
     3066760.475    13814796.556     3064952.321      13814695.5
     3064883.629    13814687.177     3064007.162    13814692.038
#Sta/Elev= 30
       0   68.85   67.81   69.02  153.21   67.88  258.38   68.29  303.45   67.49
  497.45   68.93   528.8    67.7  558.85   64.71  573.87   64.43  648.99   68.39
 1204.85   67.53 1340.83   68.62 1611.35   67.18 1715.65   69.11 1770.47   68.78
 1804.03   65.78 1818.55   65.92 1842.01   59.89 1842.84   52.52  1862.5    52.6
 1863.57   59.14 1879.03   64.24  1896.3   65.94  2031.3   67.03  2121.3   65.29
 2170.02   67.48 2406.31   67.08 2451.31   66.13 2483.29   67.57 2756.65   67.52
#Mann= 3 , 0 , 0
       0     .15       0 1818.55    .015       0  1896.3     .15       0
#XS Ineff= 2 , 0
       0    1623            1925       0
Permanent Ineff=
       T       T
Bank Sta=1818.55,1896.3
XS Rating Curve= 0
Exp/Cntr=.3,.1

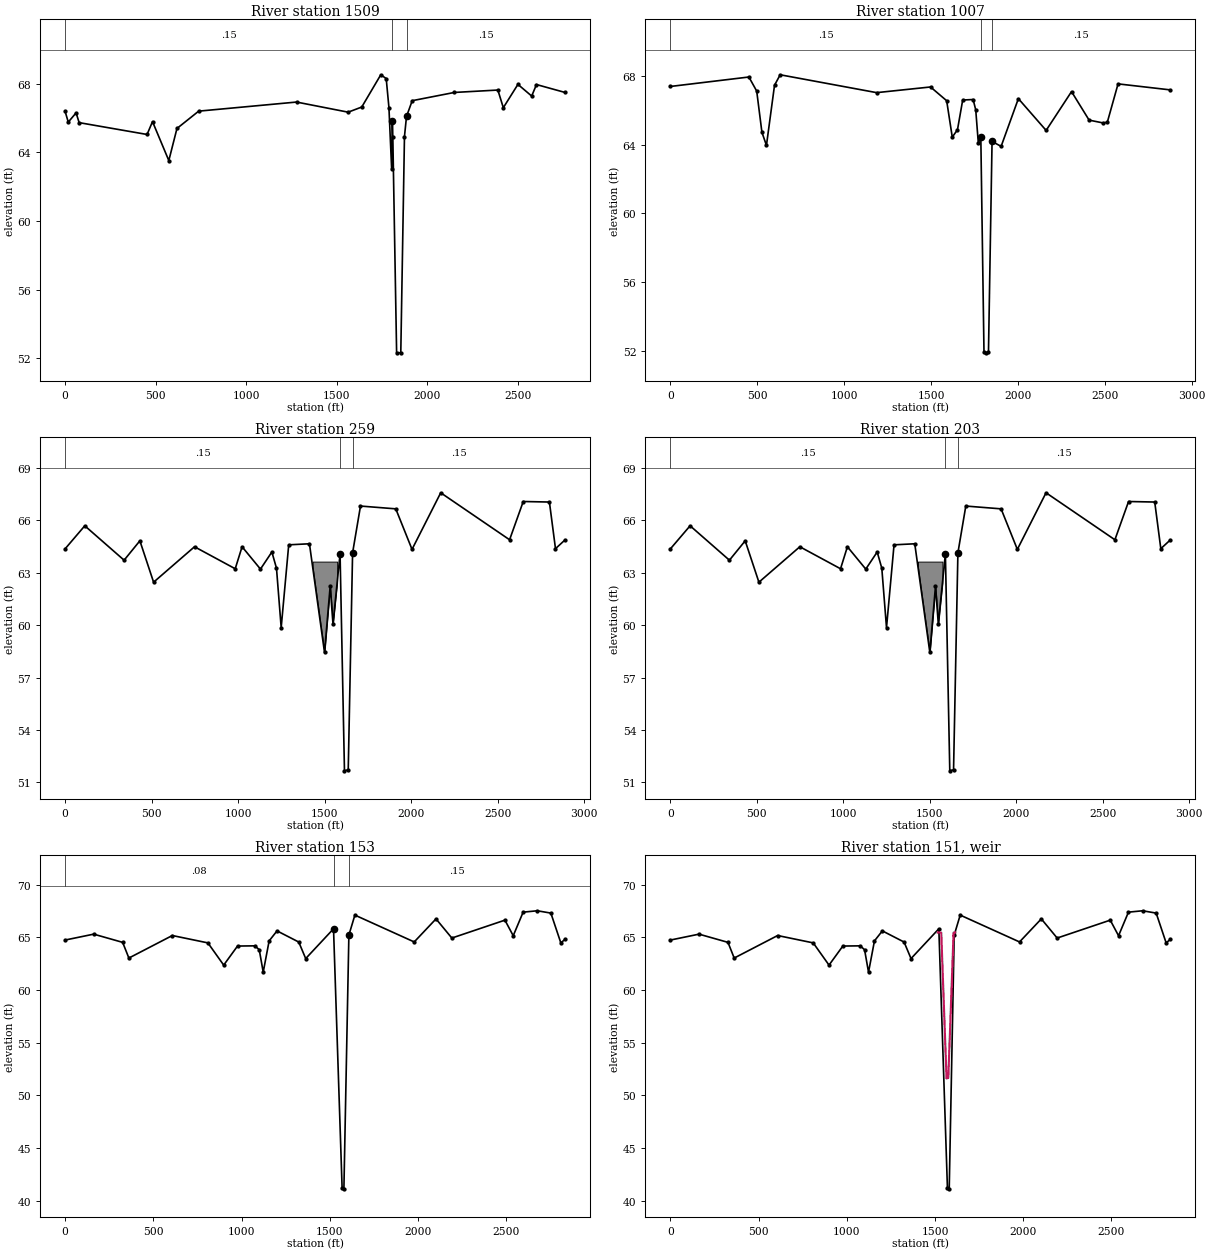
Type RM Length L Ch R = 1 ,1509    ,502.42,501.35,454.64
BEGIN DESCRIPTION:
Survey
END DESCRIPTION:
XS GIS Cut Line= 5
     3066759.988    13814590.769     3064953.674    13814546.323
     3064876.494    13814533.628     3064306.818    13814558.511
     3064008.477    13814621.602
#Sta/Elev= 30
       0    66.4   17.49   65.77   60.73   66.31   77.51   65.74  452.62   65.05
  482.63    65.8  572.66   63.53  617.67    65.4  737.59   66.41 1277.87   66.94
 1562.96   66.35 1637.98   66.65 1743.02   68.53 1773.02   68.31 1788.03   66.62
 1803.03   63.04 1806.86   65.83 1809.52   64.91 1830.48   52.32 1853.53   52.33
 1873.82   64.93 1885.08    66.1  1916.6   67.02 2149.32    67.5 2389.55   67.64
 2419.58   66.61 2500.27   67.97  2576.2   67.29 2602.81   67.96 2760.24    67.5
#Mann= 3 , 0 , 0
       0     .15       0 1806.86    .015       0 1885.08     .15       0
#XS Ineff= 2 , 0
       0    1621            1913       0
Permanent Ineff=
       T       T
Bank Sta=1806.86,1885.08
XS Rating Curve= 0
Exp/Cntr=.3,.1

Type RM Length L Ch R = 1 ,1007    ,904.67,748.06,625.47
BEGIN DESCRIPTION:
Survey
END DESCRIPTION:
XS GIS Cut Line= 4
     3066758.918    13814098.341     3064975.721    13814043.799
     3064897.771    13814036.942     3064010.202    13814529.199
#Sta/Elev= 30
       0   67.38  451.63   67.93  496.65   67.11  526.66   64.71  552.73   63.95
  599.18   67.45  631.71   68.06 1186.97   67.02 1497.04   67.35 1589.93   66.55
 1622.18   64.43 1652.19   64.86  1682.2   66.59 1742.23   66.62 1757.24   66.02
 1772.25   64.07 1786.47   64.45 1804.75   51.92  1817.2   51.87 1830.57   51.91
 1851.19   64.18 1903.35   63.89 2002.65   66.67 2162.39   64.82 2308.56   67.08
 2409.81   65.42 2488.11   65.26 2514.39   65.29 2576.38   67.53 2877.22   67.18
#Mann= 3 , 0 , 0
       0     .15       0 1786.47    .015       0 1851.19     .15       0
#XS Ineff= 2 , 0
       0    1606            1905       0
Permanent Ineff=
       T       T
Bank Sta=1786.47,1851.19
XS Rating Curve= 0
Exp/Cntr=.3,.1

Type RM Length L Ch R = 1 ,259     ,56,56,56
BEGIN DESCRIPTION:
Survey
END DESCRIPTION:
XS GIS Cut Line= 4
     3065197.548    13812282.201     3064365.109    13813621.654
     3064310.894    13813708.725     3063732.031    13814771.677
#Sta/Elev= 30
       0   64.37  113.76   65.69   341.1   63.72  432.29   64.83   511.6   62.46
  748.15   64.49  983.47   63.23 1023.12   64.49 1129.37   63.21  1195.4   64.19
 1222.04   63.26 1249.18   59.86 1292.74    64.6 1412.55   64.66 1499.69   58.44
 1532.36   62.22 1548.61   60.08 1589.58   64.08 1615.03   51.66  1636.8   51.72
 1661.98   64.14 1707.63   66.82 1911.65   66.66 2005.59   64.34 2171.46   67.58
 2569.55   64.89 2648.54   67.08 2799.82   67.05 2834.94   64.38 2889.97   64.88
#Mann= 3 , 0 , 0
       0     .15       0 1589.58    .015       0 1661.98     .15       0
#XS Ineff= 2 , 0
       0     991            1763       0
Permanent Ineff=
       T       T
#Block Obstruct= 1 ,-1
 1430.99 1572.64   63.64
Bank Sta=1589.58,1661.98
XS Rating Curve= 0
Exp/Cntr=.3,.1

Type RM Length L Ch R = 1 ,203     ,50,50,50
BEGIN DESCRIPTION:
Survey
END DESCRIPTION:
XS GIS Cut Line= 4
       3065142.8      13812259.3       3064310.3      13813598.8
       3064256.9      13813684.6       3063678.8      13814746.2
#Sta/Elev= 30
       0   64.37  113.76   65.69   341.1   63.72  432.29   64.83   511.6   62.46
  748.15   64.49  983.47   63.23 1023.12   64.49 1129.37   63.21  1195.4   64.19
 1222.04   63.26 1249.18   59.86 1292.74    64.6 1412.55   64.66 1499.69   58.44
 1532.36   62.22 1548.61   60.08 1589.58   64.08 1615.03   51.66  1636.8   51.72
 1661.98   64.14 1707.63   66.82 1911.65   66.66 2005.59   64.34 2171.46   67.58
 2569.55   64.89 2648.54   67.08 2799.82   67.05 2834.94   64.38 2889.97   64.88
#Mann= 3 , 0 , 0
       0     .15       0 1589.58    .015       0 1661.98     .15       0
#XS Ineff= 2 , 0
       0     991            1763       0
Permanent Ineff=
       T       T
#Block Obstruct= 1 ,-1
 1430.99 1572.64   63.64
Bank Sta=1589.58,1661.98
XS Rating Curve= 0
Exp/Cntr=.5,.3

Type RM Length L Ch R = 1 ,153     ,3,3,3
BEGIN DESCRIPTION:
Survey
END DESCRIPTION:
XS GIS Cut Line= 4
       3065100.3      13812232.9       3064267.9      13813572.4
       3064213.7      13813659.4       3063634.9      13814722.3
#Sta/Elev= 30
       0   64.75  162.15   65.31   326.2   64.53  361.49   63.04  607.82   65.18
  809.36   64.48  898.93   62.37  977.31   64.18 1075.74    64.2 1100.48   63.83
 1122.87    61.7 1156.46   64.67 1201.25   65.62 1324.41   64.56 1363.72   62.99
  1521.4   65.82 1570.16   41.16 1580.21   41.12 1608.46   65.22 1642.46   67.12
 1978.78   64.57 2102.24   66.76 2192.04   64.94 2492.92   66.64 2539.98   65.16
  2596.1    67.4 2676.35   67.53 2753.24   67.31 2809.76   64.48 2833.44   64.82
#Mann= 3 , 0 , 0
       0     .08       0  1521.4    .015       0 1608.46     .15       0
#XS Ineff= 2 , 0
       0     900            1836       0
Permanent Ineff=
       T       T
Bank Sta=1521.4,1608.46
XS Rating Curve= 0
Exp/Cntr=.5,.3

Type RM Length L Ch R = 5 ,151     ,,,
BEGIN DESCRIPTION:
Weir at Mouth
END DESCRIPTION:
IW Pilot Flow=0
#Inline Weir SE= 6
    1515   65.46    1535   65.46    1565    51.6    1575   51.65    1605   65.46
    1615   65.46
IW Dist,WD,Coef,Skew,MaxSub,Min_El,Is_Ogee,SpillHt,DesHd
1,1.5,3,0,.95,, 0 ,,,0,0,

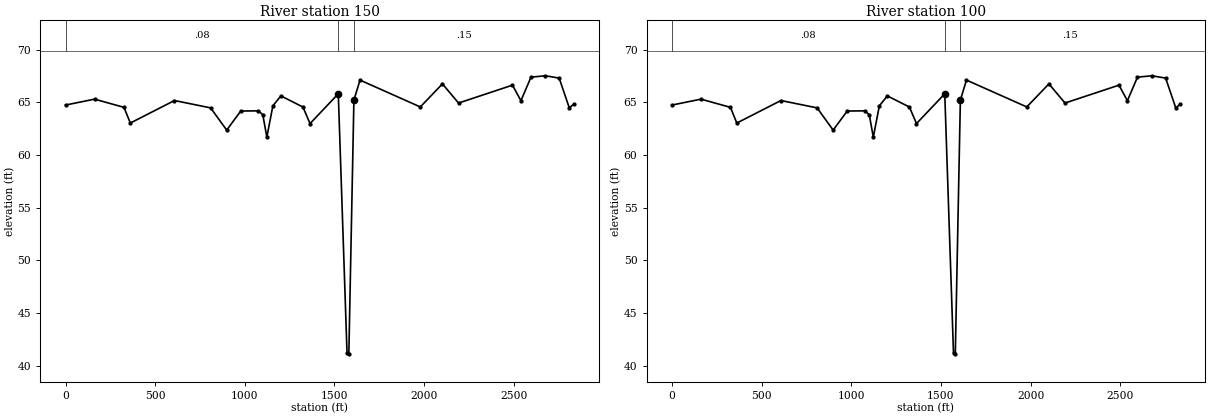
Type RM Length L Ch R = 1 ,150     ,50,50,50
BEGIN DESCRIPTION:
Survey
END DESCRIPTION:
XS GIS Cut Line= 4
       3065097.8      13812231.3       3064265.3      13813570.8
       3064211.1      13813657.9       3063632.3      13814720.8
#Sta/Elev= 30
       0   64.75  162.15   65.31   326.2   64.53  361.49   63.04  607.82   65.18
  809.36   64.48  898.93   62.37  977.31   64.18 1075.74    64.2 1100.48   63.83
 1122.87    61.7 1156.46   64.67 1201.25   65.62 1324.41   64.56 1363.72   62.99
  1521.4   65.82 1570.16   41.16 1580.21   41.12 1608.46   65.22 1642.46   67.12
 1978.78   64.57 2102.24   66.76 2192.04   64.94 2492.92   66.64 2539.98   65.16
  2596.1    67.4 2676.35   67.53 2753.24   67.31 2809.76   64.48 2833.44   64.82
#Mann= 3 , 0 , 0
       0     .08       0  1521.4    .015       0 1608.46     .15       0
#XS Ineff= 2 , 0
       0     900            1836       0
Permanent Ineff=
       T       T
Bank Sta=1521.4,1608.46
XS Rating Curve= 0
Exp/Cntr=.5,.3

Type RM Length L Ch R = 1 ,100     ,0,0,0
BEGIN DESCRIPTION:
Survey
END DESCRIPTION:
XS GIS Cut Line= 4
       3065055.3      13812204.9       3064222.9      13813544.4
       3064167.9      13813632.7       3063588.3      13814696.9
#Sta/Elev= 30
       0   64.75  162.15   65.31   326.2   64.53  361.49   63.04  607.82   65.18
  809.36   64.48  898.93   62.37  977.31   64.18 1075.74    64.2 1100.48   63.83
 1122.87    61.7 1156.46   64.67 1201.25   65.62 1324.41   64.56 1363.72   62.99
  1521.4   65.82 1570.16   41.16 1580.21   41.12 1608.46   65.22 1642.46   67.12
 1978.78   64.57 2102.24   66.76 2192.04   64.94 2492.92   66.64 2539.98   65.16
  2596.1    67.4 2676.35   67.53 2753.24   67.31 2809.76   64.48 2833.44   64.82
#Mann= 3 , 0 , 0
       0     .08       0  1521.4    .015       0 1608.46     .15       0
#XS Ineff= 2 , 0
       0     900            1836       0
Permanent Ineff=
       T       T
Bank Sta=1521.4,1608.46
XS Rating Curve= 0
Exp/Cntr=.3,.1

Chan Stop Cuts=-1